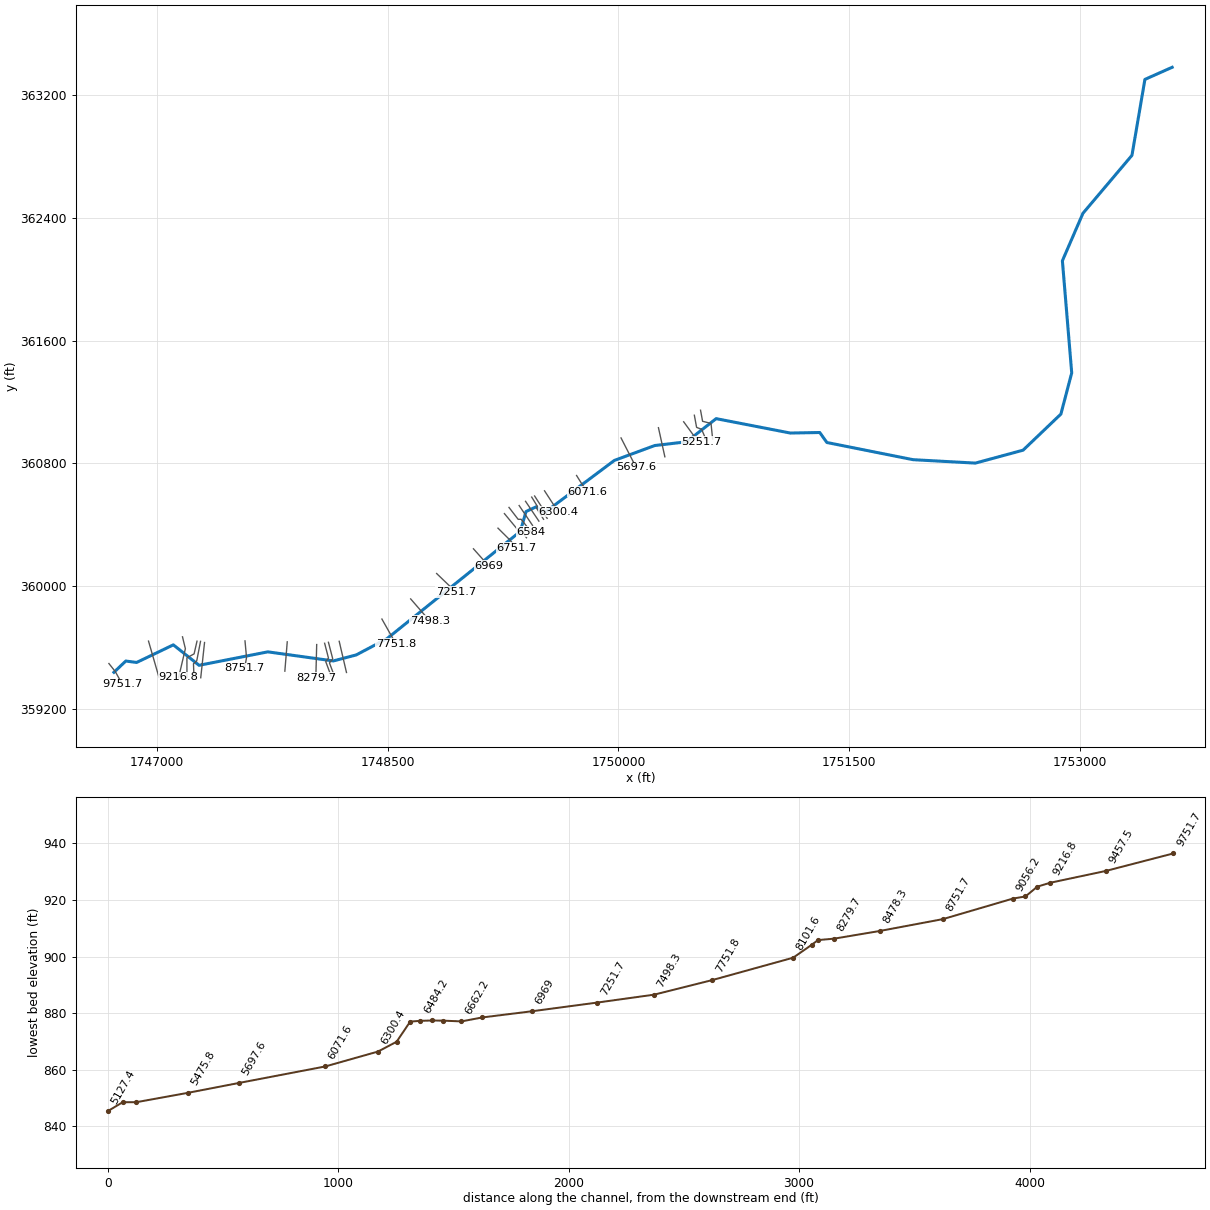
--- JACKSBR.prj (project) ---

Proj Title=JACKSBR
Current Plan=p01
Default Exp/Contr=0,0
English Units
Geom File=g01
Flow File=f01
Plan File=p01
BEGIN DESCRIPTION:
END DESCRIPTION:
DSS Export Rating Curves= 0
DSS Export Rating Curve Sorted= 0
DSS Export Volume Flow Curves= 0
DXF OffsetX= 0
DXF OffsetY= 0
DXF ScaleX= 0
DXF ScaleY= 0

--- JACKSBR.p01 (plan) ---

Plan Title=Floodplain
Program Version=4.00
Geom File=g01
Flow File=f01
K Sum by GR=0
Std Step Tol=0.01
Critical Tol=0.01
Num of Std Step Trials=20
Max Error Tol=0.3
Flow Tol Ratio=0.001
Split Flow NTrial=30
Split Flow Tol=0.02
Split Flow Ratio=0.02
Log Output Level=0
Friction Slope Method=1
Unsteady Friction Slope Method=2
Unsteady Bridges Friction Slope Method=1
Global Log Level=0
CheckData=False
Run HTab=0
Run UNet=0
Run PostProcess=0
UNET Theta=0
UNET Theta Warmup=0
UNET ZTol=0
UNET ZSATol=0
UNET MxIter=0
UNET MaxInSteps=0
UNET DtIC=0
UNET DtMin=0
UNET MaxCRTS=0
UNET WFStab=0
UNET SFStab=0
UNET WFX=0
UNET SFX=0
UNET DSS MLevel=0
UNET DZMax Abort=0
UNET Convert EG Bridges=0
UNET Use Existing IB Tables=0
UNET Froude Limit=0
UNET Froude Power=0
Write IC File=0
Echo Input=False
Echo Output=False
Write Detailed=0

--- JACKSBR.f01 (steady flow) ---

Flow Title=NFF Regression Equation
Program Version=4.00
Number of Profiles=1
Profile Names=P100yr
River Rch & RM=JACKSBR,Main      ,9751.7
889.5818
River Rch & RM=JACKSBR,Main      ,9216.8
928.1571
River Rch & RM=JACKSBR,Main      ,6969
1009.558
River Rch & RM=JACKSBR,Main      ,4966.4
1120.875
River Rch & RM=JACKSBR,Main      ,899.4
1241.739
River Rch & RM=JACKSBR,Main      ,595.3
1244.205
Boundary for River Rch & Prof#=JACKSBR,Main      ,1
Up Type=0
Dn Type=3
Dn Slope=0.004139

--- JACKSBR.g01 (geometry) ---

Geom Title=USGS 10m DEM
Program Version=4.10

River Reach=JACKSBR         ,Main
Reach XY= 30
     1746721.113      359439.463     1746798.034      359512.823
     1746868.546      359503.564     1747107.144      359618.234
      1747274.52      359485.046     1747721.092      359572.651
     1748147.009      359513.535     1748295.866      359552.708
     1748496.004      359658.831     1749362.083      360356.822
     1749399.325      360486.523     1749466.069      360517.645
     1749519.487      360479.184     1749973.181      360819.277
     1750235.404      360916.222     1750442.001      360940.528
     1750634.709      361091.395      1751116.48      360997.646
     1751307.994      361001.108     1751354.327      360936.013
     1751914.691      360824.098     1752319.605      360801.899
     1752629.501        360886.1     1752875.161       361121.17
     1752945.473      361389.399     1752884.862      362119.583
      1753018.39      362428.635     1753336.966      362806.239
     1753421.168      363300.597     1753598.251       363379.59

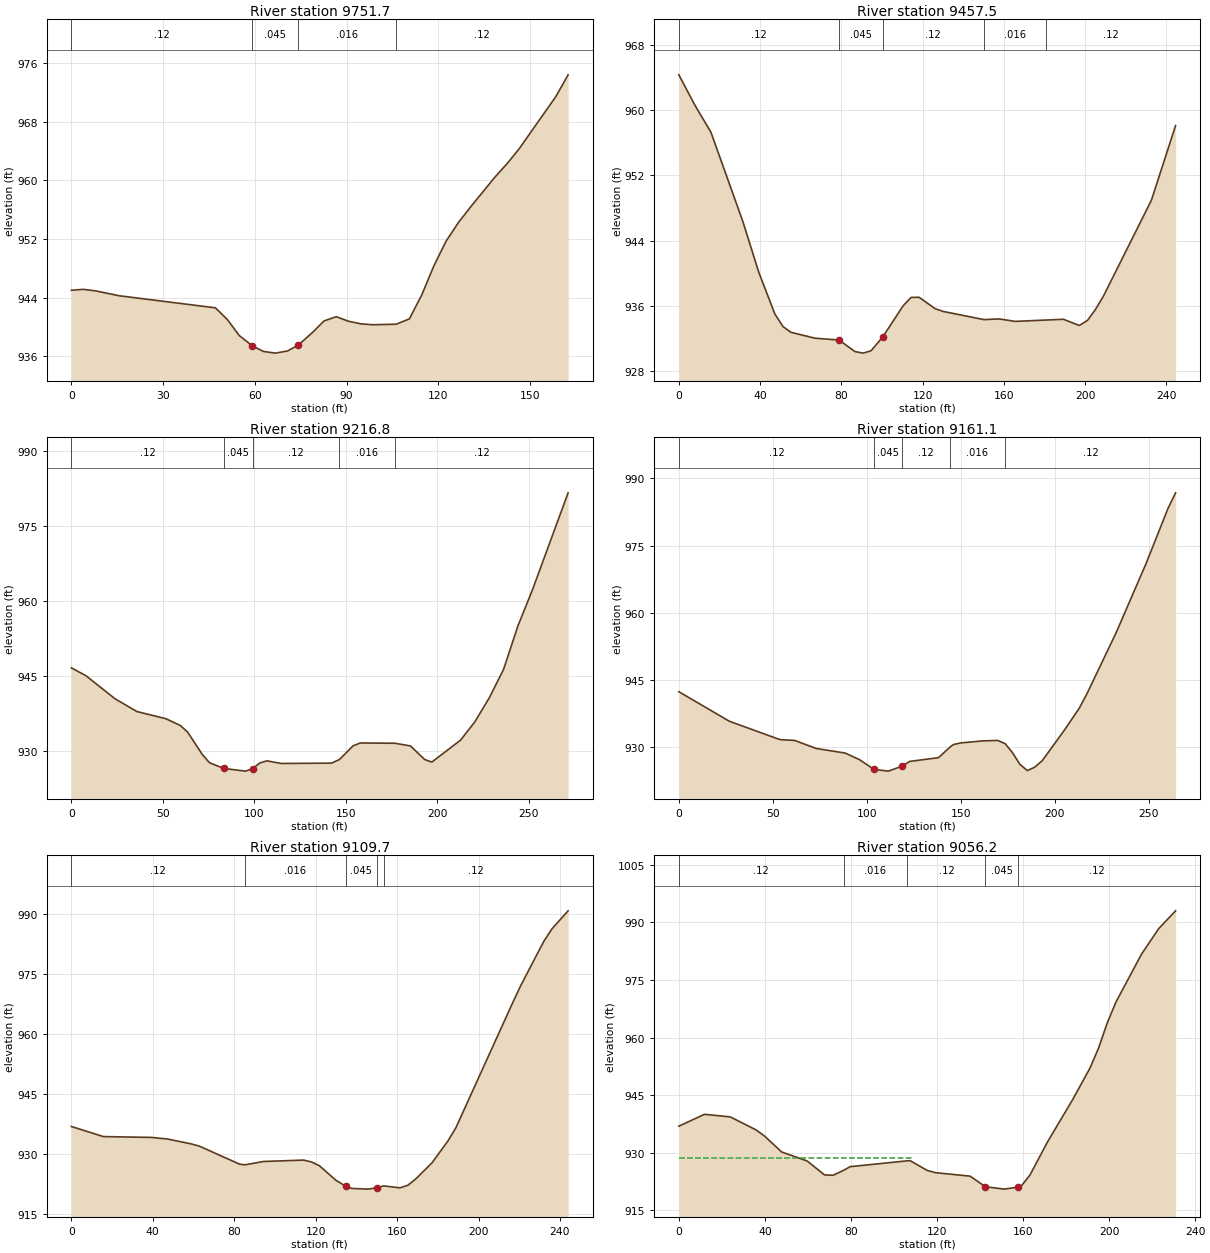
Type RM Length L Ch R = 1 ,9751.7  ,301.5,294.2,286.6
XS GIS Cut Line= 3
       1746688.5      359496.592     1746729.865      359444.299
      1746776.16      359360.529
#Sta/Elev= 30
       0  944.99     3.9  945.12     7.8  944.92    15.7  944.24    47.1   942.6
      51     941    54.9  938.81    59.2   937.4    62.8  936.65    66.7  936.42
    70.7  936.72    74.2  937.52    78.6  939.15    82.6  940.81    86.6  941.39
    90.6  940.77    94.6  940.42    98.6  940.29  106.19940.3659   110.5  941.09
   114.5  944.31   118.5  948.31   122.5  951.69   126.5  954.21   130.5  956.35
   138.5  960.44   142.4  962.24   146.4  964.29   158.4  971.42   162.4  974.38
#Mann= 4 ,-1 , 0
       0     .12       0    59.2    .045       0    74.2    .016       0
  106.19     .12       0
Bank Sta=59.2,74.2
XS Rating Curve= 0 ,0
Exp/Cntr=0.3,0.1

Type RM Length L Ch R = 1 ,9457.5  ,249.1,240.7,228.7
XS GIS Cut Line= 2
     1746945.829      359642.618     1747013.537      359407.722
#Sta/Elev= 30
       0  964.32     7.9   960.6    15.8  957.28    31.5  946.35    39.4  940.08
    47.3  934.99    51.3  933.46    55.2  932.76      67  932.04    78.9  931.81
    86.7   930.4    90.7  930.21    94.6   930.5   100.3  932.17   110.4  936.01
   114.3  937.04   118.3  937.05   126.2  935.65   130.1  935.32  150.18934.3167
   157.7   934.4   165.6   934.1  180.92934.2664   189.3  934.36   197.1   933.6
   201.1  934.21     205  935.54     209   937.2   232.6  948.95   244.5   958.1
#Mann= 5 ,-1 , 0
       0     .12       0    78.9    .045       0   100.3     .12       0
  150.18    .016       0  180.92     .12       0
Bank Sta=78.9,100.3
XS Rating Curve= 0 ,0
Exp/Cntr=0.3,0.1

Type RM Length L Ch R = 1 ,9216.8  ,78.3,55.7,35.2
XS GIS Cut Line= 3
     1747166.685      359670.366     1747185.349      359593.109
     1747141.512      359406.044
#Sta/Elev= 30
       0  946.67       8  945.09    23.8  940.51    35.8  937.95    51.7  936.51
    59.6  935.16    63.6  933.83    71.5  929.42    75.5  927.73    83.4  926.58
    95.2  926.05    99.1  926.53     103  927.68   106.9   928.1   114.8  927.58
   142.2  927.64  146.52 928.356     154  931.09   157.9  931.67  176.85931.6166
   185.4  931.08   193.2  928.36   197.1  927.86   212.8  932.24   220.6  935.89
   228.5  940.68   236.3  946.36   244.2  955.09     252  962.14   271.6  981.61
#Mann= 5 ,-1 , 0
       0     .12       0    83.4    .045       0    99.1     .12       0
  146.52    .016       0  176.85     .12       0
Bank Sta=83.4,99.1
XS Rating Curve= 0 ,0
Exp/Cntr=0.3,0.1

Type RM Length L Ch R = 1 ,9161.1  ,38.8,51.4,66.7
XS GIS Cut Line= 4
     1747260.869      359642.155     1747242.136      359559.627
     1747195.308      359533.764     1747195.829      359407.722
#Sta/Elev= 30
       0   942.4    26.9   935.8    53.8  931.71    61.6  931.53    73.1  929.73
    88.4  928.72    96.1  927.24   103.8  925.07   111.4  924.68   118.8   925.8
   122.8  926.85   138.1  927.68  144.05 929.975     146   930.6   149.9  930.97
   161.8  931.43   169.6  931.53  173.58930.8036   177.5  928.78   181.4  926.19
   185.4  924.79   189.3  925.57   193.3  927.02   205.1  933.85     213  938.74
   216.9  941.81   232.6  955.58   248.4   970.9   260.2  983.32   264.2  986.78
#Mann= 5 ,-1 , 0
       0     .12       0   103.8    .045       0   118.8     .12       0
  144.05    .016       0  173.58     .12       0
Bank Sta=103.8,118.8
XS Rating Curve= 0 ,0
Exp/Cntr=0.3,0.1

Type RM Length L Ch R = 1 ,9109.7  ,43.3,53.5,60.6
XS GIS Cut Line= 4
      1747283.85      359641.055     1747259.133      359513.682
     1747238.016      359495.743     1747241.141      359409.284
#Sta/Elev= 30
       0  936.86    15.7  934.34    39.3  934.13    47.2  933.73      59   932.5
    62.9  931.94    82.6  927.46   85.25927.2833    94.4  928.12     114  928.47
     118     928   121.9  927.04   129.8  923.49   134.9  921.89   137.7   921.4
   145.6  921.22   149.9  921.53   153.5  922.03   161.4  921.54   165.3  922.19
   169.2  923.78   177.1  927.76     185  933.26   188.9  936.57   216.4  967.34
   220.4  971.69   228.2  979.33   232.2  983.19   236.1  986.22     244   990.7
#Mann= 5 ,-1 , 0
       0     .12       0   85.25    .016       0   134.9    .045       0
   149.9    .016       0   153.5     .12       0
Bank Sta=134.9,149.9
XS Rating Curve= 0 ,0
Exp/Cntr=0.3,0.1

Type RM Length L Ch R = 1 ,9056.2  ,299.5,304.5,302.9
XS GIS Cut Line= 2
     1747309.915      359633.474     1747285.175      359403.873
#Sta/Elev= 30
       0   936.9    11.9  939.99    23.9  939.32    35.8  935.95    39.8  934.34
    47.8  930.17    59.7  927.81    67.7   924.2    71.7   924.1   76.55925.3793
    79.6  926.34  106.25927.8694   107.5  927.91   115.5  925.35   119.4  924.77
   135.4  923.87   142.5  921.11   151.3  920.49   157.5  921.01   159.3   921.4
   163.2  924.14   171.2  932.63   183.2  943.96   191.1  952.03   195.1  957.25
   199.1  963.75   203.1  969.15     215  981.67     223  988.35   230.9  993.03
#Mann= 5 ,-1 , 0
       0     .12       0   76.55    .016       0  106.25     .12       0
   142.5    .045       0   157.5     .12       0
#XS Ineff= 2 , 0
          107.74  928.59
Permanent Ineff=
       F       F
Bank Sta=142.5,157.5
XS Rating Curve= 0 ,0
Exp/Cntr=0.3,0.1

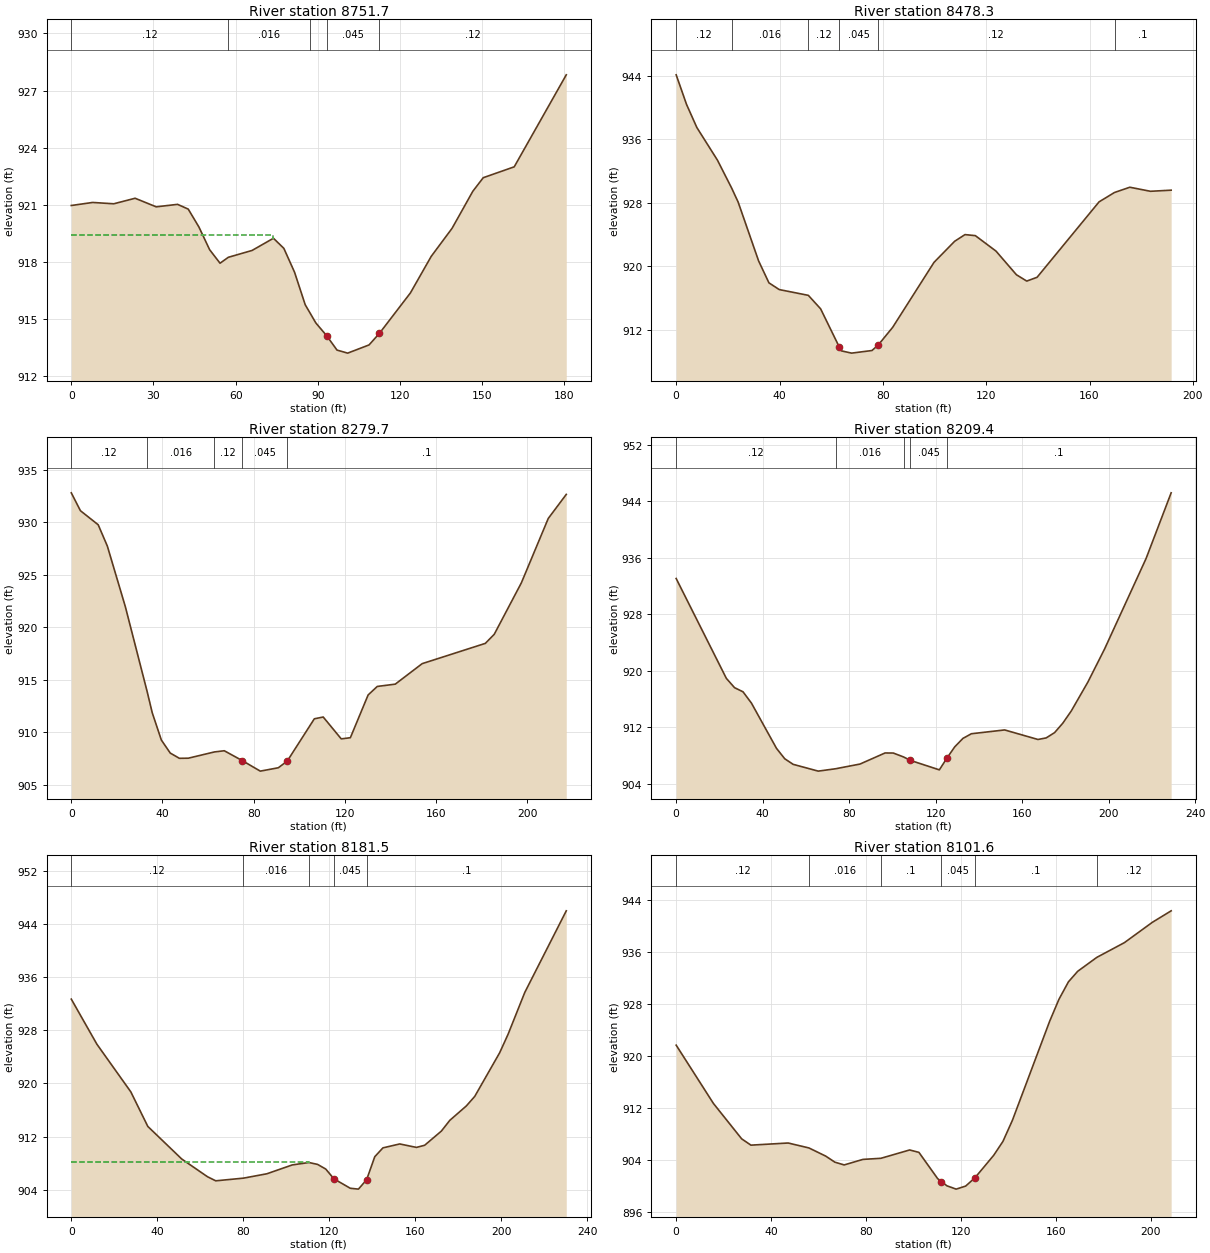
Type RM Length L Ch R = 1 ,8751.7  ,277.5,273.4,275.3
XS GIS Cut Line= 3
     1747572.815      359643.985     1747582.818      359535.768
     1747570.287       359464.86
#Sta/Elev= 30
       0  920.97     7.8  921.13    15.5  921.06    23.3  921.35      31   920.9
    38.8  921.03    42.7  920.78    46.6  919.84    50.5  918.65    54.3  917.94
   57.33918.2508      66  918.61    73.8  919.25    77.6  918.72    81.5  917.47
    85.4  915.76      87915.3661    89.3   914.8    93.2  914.14      97  913.38
   100.9  913.22   108.7  913.65   112.5  914.26   123.8  916.38   131.4   918.3
     139  919.77   146.6  921.72   150.4  922.43   161.7     923   180.7  927.83
#Mann= 5 ,-1 , 0
       0     .12       0   57.33    .016       0      87     .12       0
    93.2    .045       0   112.5     .12       0
#XS Ineff= 2 , 0
           73.48  919.43
Permanent Ineff=
       F       F
Bank Sta=93.2,112.5
XS Rating Curve= 0 ,0
Exp/Cntr=0.3,0.1

Type RM Length L Ch R = 1 ,8478.3  ,197.3,198.6,199.8
XS GIS Cut Line= 2
     1747847.426      359637.861     1747831.801      359446.889
#Sta/Elev= 30
       0  944.12       4   940.4       8  937.48      16  933.35   21.51929.8192
      24  928.07    31.9  920.67    35.9   917.9    39.9  917.05   51.15916.3244
    55.9  914.63    63.2  909.77    63.9  909.33    67.9  909.04    75.8  909.37
    78.2  910.06    83.8  912.29    99.8  920.48   107.8  923.14   111.8  923.98
   115.8  923.85   123.8   921.9   131.7  918.92   135.7  918.12   139.7   918.6
   163.7  928.11  169.68  929.29   175.6  929.95   183.6  929.44   191.6  929.58
#Mann= 6 ,-1 , 0
       0     .12       0   21.51    .016       0   51.15     .12       0
    63.2    .045       0    78.2     .12       0  169.68      .1       0
Bank Sta=63.2,78.2
XS Rating Curve= 0 ,0
Exp/Cntr=0.3,0.1

Type RM Length L Ch R = 1 ,8279.7  ,76.7,70.3,66.7
XS GIS Cut Line= 2
     1748038.763      359620.103     1748033.121      359403.089
#Sta/Elev= 30
       0  932.81       4  931.11    11.8  929.77    15.8  927.75    23.7  921.98
   33.24913.9199    35.5  911.88    39.5  909.28    43.4  908.04    47.4  907.54
    51.3  907.55   62.78908.1458    67.1  908.26      75  907.32    82.9  906.32
    90.8  906.64    94.7  907.27   106.6   911.3   110.5  911.47   118.4  909.39
   122.4   909.5   130.2  913.57   134.2  914.38   142.1   914.6   153.9  916.55
   181.6  918.48   185.5  919.34   197.4  924.24   209.2  930.37   217.1  932.66
#Mann= 5 ,-1 , 0
       0     .12       0   33.24    .016       0   62.78     .12       0
      75    .045       0    94.7      .1       0
Bank Sta=75,94.7
XS Rating Curve= 0 ,0
Exp/Cntr=0.3,0.1

Type RM Length L Ch R = 1 ,8209.4  ,28,27.9,22.6
XS GIS Cut Line= 4
     1748090.296        359628.7      1748115.47      359531.478
     1748097.458      359509.598     1748132.079      359415.676
#Sta/Elev= 30
       0  933.07    23.2  918.94      27  917.62    30.9  917.04    34.8  915.44
    46.4  909.03    50.2  907.56    54.1  906.77    65.7  905.81   73.71 906.145
      85  906.81    96.6  908.38   100.4  908.37  105.19907.8122   108.2  907.34
   121.7  905.99   125.2  907.65   128.8  909.24   132.6  910.44   136.5   911.1
   151.9  911.64   167.3  910.29   171.1  910.51     175  911.26   178.8   912.6
   182.7  914.32   190.4  918.42   198.1  923.09   217.3   935.9   228.9   945.2
#Mann= 5 ,-1 , 0
       0     .12       0   73.71    .016       0  105.19      .1       0
   108.2    .045       0   125.2      .1       0
Bank Sta=108.2,125.2
XS Rating Curve= 0 ,0
Exp/Cntr=0.3,0.1

Type RM Length L Ch R = 1 ,8181.5  ,67.6,79.9,94.6
XS GIS Cut Line= 4
     1748115.152       359634.86      1748142.93      359527.655
     1748121.662      359500.745      1748151.61      359420.884
#Sta/Elev= 30
       0   932.7    11.9  925.92    27.7  918.74    35.6  913.54    51.4  908.63
    63.3  905.98    67.2  905.35   80.08905.7516      91  906.41   102.8  907.74
  110.59908.1063   114.6  907.82   118.4  907.12   122.2  905.65   129.8  904.23
   133.6   904.1   137.4  905.51   141.2  908.98     145  910.31   152.8   910.9
   160.6  910.38   164.4   910.7   172.2  912.84   176.1  914.45   183.8  916.62
   187.7  918.05   199.3  924.62   203.2  927.39     211  933.71   230.3  945.99
#Mann= 5 ,-1 , 0
       0     .12       0   80.08    .016       0  110.59      .1       0
   122.2    .045       0   137.4      .1       0
#XS Ineff= 2 , 0
       0  110.59  908.11               0
Permanent Ineff=
       F       F
Bank Sta=122.2,137.4
XS Rating Curve= 0 ,0
Exp/Cntr=0.3,0.1

Type RM Length L Ch R = 1 ,8101.6  ,343.3,349.8,356
XS GIS Cut Line= 2
      1748185.03       359641.37     1748232.339      359438.245
#Sta/Elev= 30
       0  921.72    15.7  912.76    27.6  907.32    31.5  906.35    47.2  906.68
   55.96905.9179      63  904.67    66.9  903.73    70.8  903.31    78.7  904.16
   86.28904.3288    98.4  905.61   102.3  905.24   110.2   901.2   111.8  900.75
   114.1   900.1     118  899.59     122  900.06   125.9  901.33   133.8  904.78
   137.7  906.92   141.7  910.17   157.4   925.4   161.3  928.76   165.3  931.45
   169.2  933.07  177.26935.2116   188.9  937.48   200.7  940.61   208.6  942.37
#Mann= 6 ,-1 , 0
       0     .12       0   55.96    .016       0   86.28      .1       0
   111.8    .045       0   125.9      .1       0  177.26     .12       0
#XS Ineff= 2 , 0
       0    98.4  905.61               0
Permanent Ineff=
       F       F
Bank Sta=111.8,125.9
XS Rating Curve= 0 ,0
Exp/Cntr=0.3,0.1

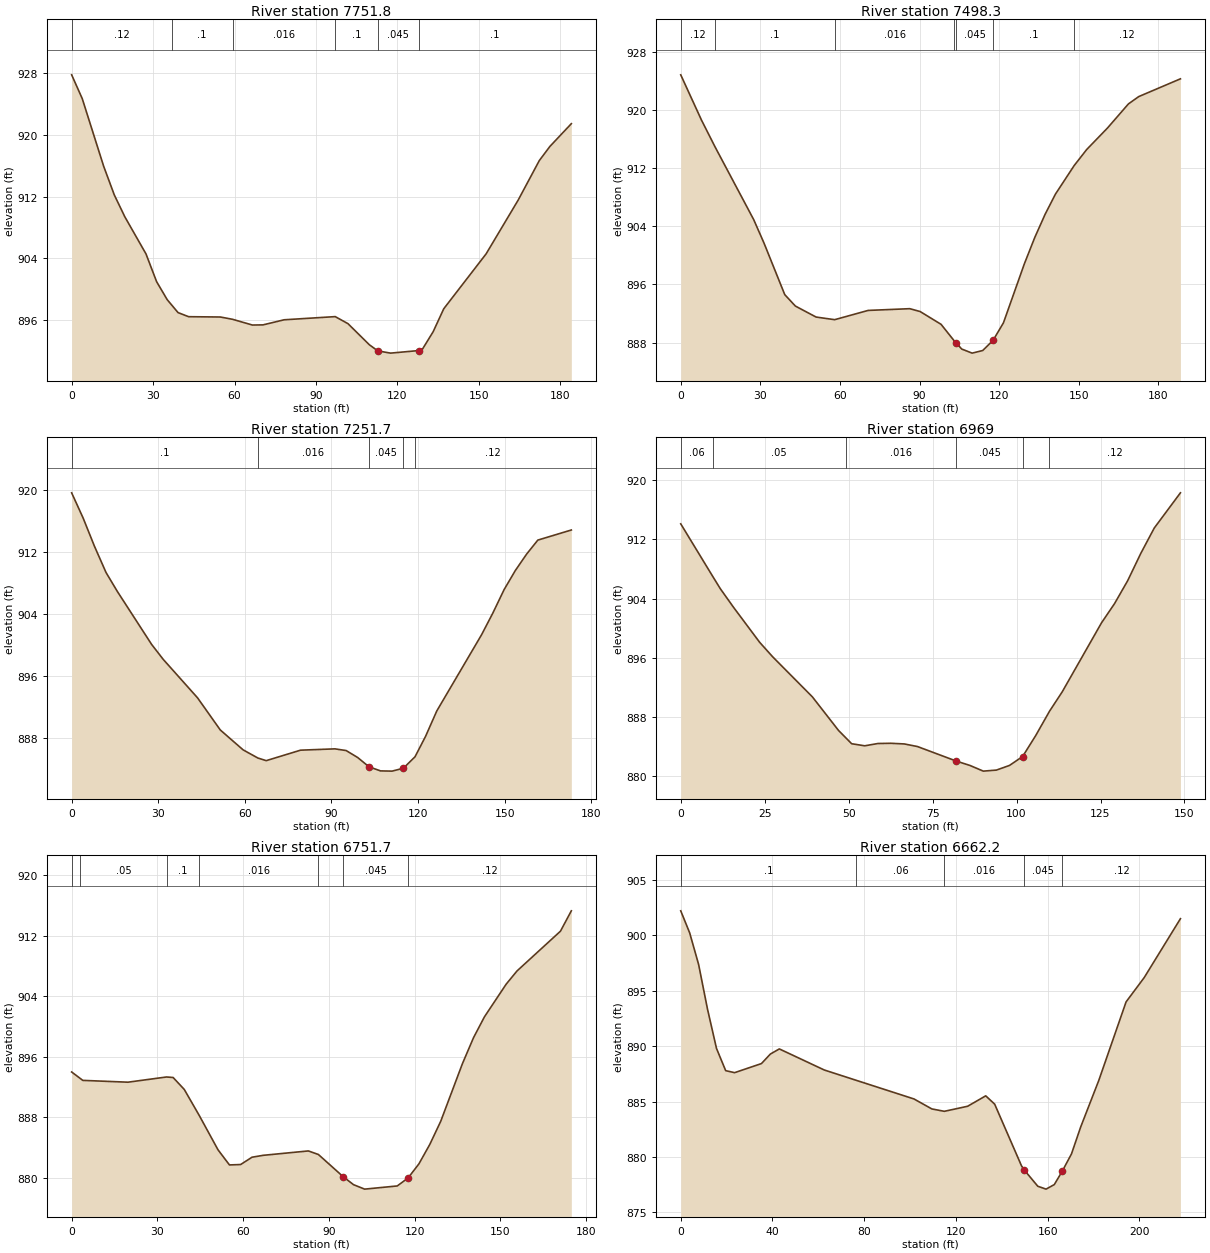
Type RM Length L Ch R = 1 ,7751.8  ,248.9,253.4,257.9
XS GIS Cut Line= 2
     1748462.634      359786.205     1748552.912      359625.788
#Sta/Elev= 30
       0  927.77     3.9  924.69    11.8  915.92    15.7  912.22    19.6  909.37
    27.4  904.56    31.3  900.97    35.2  898.64   36.89897.9302    39.2  896.96
    43.1  896.43    54.8  896.39   59.28896.0933    66.6  895.35    70.5  895.37
    78.3  896.03   97.11896.4404   101.8  895.53   109.7  892.79   112.8     892
   117.5  891.71   127.8  892.04   129.2   892.2   133.2  894.49   137.1  897.46
   152.7  904.57   164.5  911.53   172.3  916.66   176.2  918.49   184.1  921.44
#Mann= 6 ,-1 , 0
       0     .12       0   36.89      .1       0   59.28    .016       0
   97.11      .1       0   112.8    .045       0   127.8      .1       0
#XS Ineff= 2 , 0
       0   94.42                       0
Permanent Ineff=
       F       F
Bank Sta=112.8,127.8
XS Rating Curve= 0 ,0
Exp/Cntr=0.3,0.1

Type RM Length L Ch R = 1 ,7498.3  ,244.7,246.6,248.7
XS GIS Cut Line= 2
      1748649.51      359917.375     1748772.773      359775.014
#Sta/Elev= 30
       0   924.8     7.8  918.59   12.89914.9225    27.5  904.89    31.4  901.65
    39.2  894.58    43.2  893.01      51   891.5   58.01 891.138    70.6  892.41
    86.3  892.65    90.2  892.26    98.1   890.5  103.13 888.194   103.9  887.89
   105.9   887.1   109.8  886.54   113.8   886.9   117.7   888.3   121.6   890.7
   129.5  898.83   133.4  902.43   137.3  905.62   141.2   908.4  148.25912.3219
     153  914.54   160.8  917.48   168.7   920.8   172.6  921.81   188.3  924.25
#Mann= 7 ,-1 , 0
       0     .12       0   12.89      .1       0   58.01    .016       0
  103.13      .1       0   103.9    .045       0   117.7      .1       0
  148.25     .12       0
#XS Ineff= 2 , 0
       0   82.27                       0
Permanent Ineff=
       F       F
Bank Sta=103.9,117.7
XS Rating Curve= 0 ,0
Exp/Cntr=0.3,0.1

Type RM Length L Ch R = 1 ,7251.7  ,284.3,282.6,281
XS GIS Cut Line= 3
     1748818.222      360082.823     1748898.189      360005.875
     1748942.978      359962.777
#Sta/Elev= 30
       0  919.61       4  916.34     7.9  912.73    11.9  909.35    15.8  906.92
    27.7  900.08    31.7  898.16    43.6   893.2    51.5  889.05    59.4  886.49
    64.5885.4407    67.4   885.1    79.3  886.45    91.2  886.62    95.1   886.4
    99.1   885.5     103  884.31     107  883.78     111  883.75   114.9  884.12
  118.95885.5981   122.6  888.23   126.5  891.51     142  901.32   145.9  904.11
   149.8  907.13   153.7   909.6   157.6  911.71   161.5  913.52   173.1  914.82
#Mann= 5 ,-1 , 0
       0      .1       0    64.5    .016       0     103    .045       0
   114.9      .1       0  118.95     .12       0
Bank Sta=103,114.9
XS Rating Curve= 0 ,0
Exp/Cntr=0.3,0.1

Type RM Length L Ch R = 1 ,6969    ,215.8,217.4,216.9
XS GIS Cut Line= 2
     1749057.496      360243.764     1749156.454      360132.652
#Sta/Elev= 30
       0  914.09    9.56906.9664    11.8  905.32    15.7  902.83    23.5  898.09
    27.4  896.12    39.2  890.72      47  886.18   49.11885.2115    50.9  884.39
    54.8  884.11    58.7  884.42    62.6  884.45    66.6  884.36    70.5  884.01
    82.1  882.04    86.1  881.46    90.1  880.69      94  880.83    97.9  881.46
   101.8  882.66   105.7  885.49  109.81888.7755   113.6   891.4   125.3  900.72
   129.2  903.33   133.1  906.42     137   910.1     141  913.52   148.8  918.28
#Mann= 6 ,-1 , 0
       0     .06       0    9.56     .05       0   49.11    .016       0
    82.1    .045       0   101.8      .1       0  109.81     .12       0
Bank Sta=82.1,101.8
XS Rating Curve= 0 ,0
Exp/Cntr=0.3,0.1

Type RM Length L Ch R = 1 ,6751.7  ,87.7,89.5,94.3
XS GIS Cut Line= 3
      1749216.99      360378.162     1749289.691      360305.915
     1749337.104      360251.331
#Sta/Elev= 30
       0  893.97    3.03893.1076     3.9  892.86    19.7  892.62    33.2 893.309
    35.5  893.24    39.4  891.66   44.67888.1973    51.2  883.68    55.2  881.68
    59.1  881.73    63.1   882.7      67  882.95    82.8  883.53   86.31 883.062
      95  880.12    98.6  879.07   102.5  878.48   113.9   878.9   117.7  879.96
   121.5  881.83   125.3   884.4   129.1  887.44   136.7  895.07   140.6  898.52
   144.4  901.26     152  905.58   155.8  907.33     171  912.59   174.8  915.28
#Mann= 7 ,-1 , 0
       0      .1       0    3.03     .05       0    33.2      .1       0
   44.67    .016       0   86.31     .12       0      95    .045       0
   117.7     .12       0
#XS Ineff= 2 , 0
       0      67                       0
Permanent Ineff=
       F       F
Bank Sta=95,117.7
XS Rating Curve= 0 ,0
Exp/Cntr=0.3,0.1

Type RM Length L Ch R = 1 ,6662.2  ,71.6,78.2,74.5
XS GIS Cut Line= 4
     1749258.699      360472.924     1749353.317       360358.34
     1749371.112      360357.038     1749401.928      360315.806
#Sta/Elev= 30
       0  902.19     3.9   900.2     7.8  897.35    11.7   893.3    15.6  889.78
    19.6  887.78    23.5   887.6    35.2  888.42    39.1  889.28      43  889.74
    62.6  887.84   76.64 886.902   101.7  885.23   109.5  884.33  114.94884.1153
   125.1  884.57     133  885.51   136.9  884.76   148.6   879.2   149.9   878.8
   155.7  877.36   159.3   877.1   162.9  877.51   166.4  878.73   170.4  880.28
   174.4   882.7   182.3   886.9   194.2  893.98   202.1  896.17   217.9  901.48
#Mann= 5 ,-1 , 0
       0      .1       0   76.64     .06       0  114.94    .016       0
   149.9    .045       0   166.4     .12       0
Bank Sta=149.9,166.4
XS Rating Curve= 0 ,0
Exp/Cntr=0.3,0.1

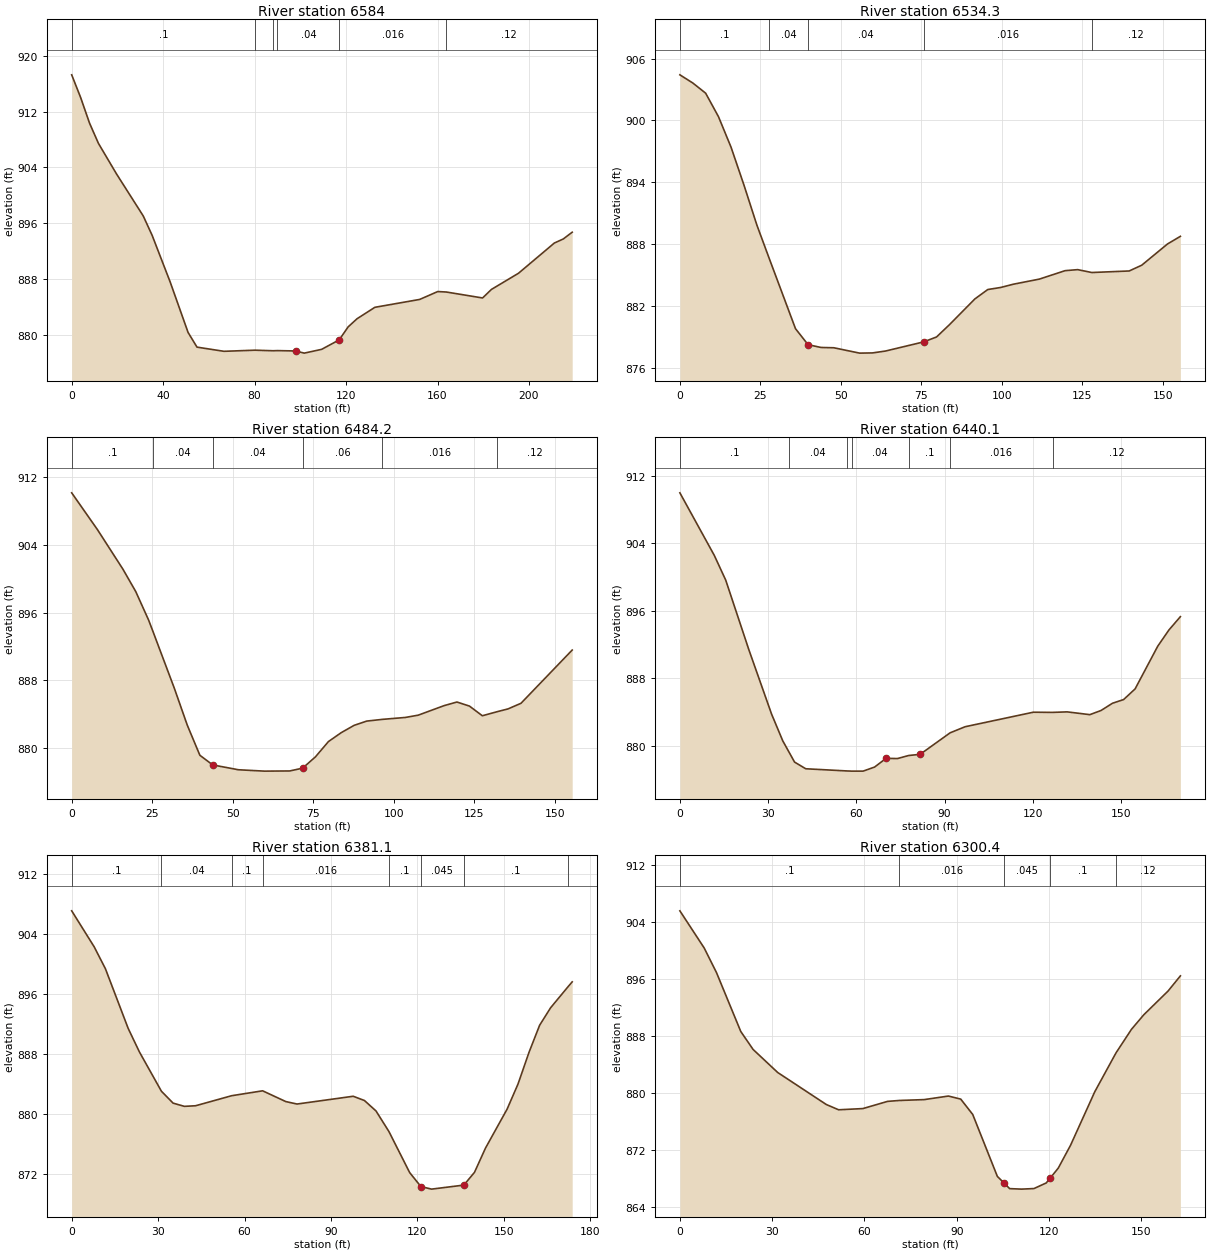
Type RM Length L Ch R = 1 ,6584    ,60.7,49.7,47.2
XS GIS Cut Line= 4
     1749288.489      360513.201     1749348.109      360435.597
     1749367.206      360436.031     1749430.574       360356.17
#Sta/Elev= 30
       0  917.27     3.9  914.03     7.8  910.35    11.7  907.44    19.6  903.06
    31.3  897.03    35.2  894.24    43.1  887.54    50.9  880.33    54.8  878.22
    66.6  877.62    80.1877.7808   88.07877.7002      90  877.72    97.9  877.67
   101.7  877.36   109.3   877.9     117  879.26   120.9  881.12   124.8  882.29
   132.6  883.93   152.2  885.06   160.1  886.19  163.86886.1225   179.7  885.27
   183.6   886.5   195.4  888.81   211.1  893.15     215  893.73   218.9   894.7
#Mann= 6 ,-1 , 0
       0      .1       0    80.1     .04       0   88.07     .06       0
      90     .04       0     117    .016       0  163.86     .12       0
Bank Sta=97.9,117
XS Rating Curve= 0 ,0
Exp/Cntr=0.3,0.1

Type RM Length L Ch R = 1 ,6534.3  ,50.1,50.1,50.1
XS GIS Cut Line= 2
     1749354.446      360525.488     1749441.251      360396.582
#Sta/Elev= 30
       0  904.42       4  903.63       8  902.64      12  900.35    15.9  897.39
    19.9  893.72    23.9  889.85   27.79886.5629    35.9  879.79    39.8  878.24
    43.8  877.97    47.8  877.94    55.8  877.42    59.8  877.44    63.8  877.62
    75.7  878.51    79.7  878.99    83.7  880.18    91.6  882.68    95.6  883.59
    99.6  883.79   103.6  884.11   111.6   884.6   119.6  885.42   123.5  885.52
  127.91  885.24   139.5  885.39   143.4  885.95   151.4  888.01   155.4  888.75
#Mann= 5 ,-1 , 0
       0      .1       0   27.79     .04       0    39.8     .04       0
    75.7    .016       0  127.91     .12       0
Bank Sta=39.8,75.7
XS Rating Curve= 0 ,0
Exp/Cntr=0.3,0.1

Type RM Length L Ch R = 1 ,6484.2  ,48.7,44.1,57.6
XS GIS Cut Line= 2
     1749396.067      360552.932     1749482.872      360424.026
#Sta/Elev= 30
       0  910.12       8  905.78    15.9  901.12    19.9  898.47    23.9   895.1
   25.27893.7368    31.9  887.04    35.9  882.71    39.8  879.17    43.8  878.03
    51.8  877.46    59.8   877.3    67.7  877.32    71.7  877.65    75.7  878.99
    79.7  880.78    83.7  881.84    87.7   882.7    91.6   883.2   96.49883.4045
   103.6  883.63   107.6   883.9   115.6  885.02   119.6  885.45   123.5  884.97
   127.5  883.83   132.1884.3085   135.5  884.64   139.5   885.3   155.4  891.58
#Mann= 6 ,-1 , 0
       0      .1       0   25.27     .04       0    43.8     .04       0
    71.7     .06       0   96.49    .016       0   132.1     .12       0
Bank Sta=43.8,71.7
XS Rating Curve= 0 ,0
Exp/Cntr=0.3,0.1

Type RM Length L Ch R = 1 ,6440.1  ,41.1,59,43.4
XS GIS Cut Line= 4
     1749436.112       360580.48     1749472.675      360520.667
     1749466.165      360511.118      1749513.04      360436.031
#Sta/Elev= 30
       0  909.99    11.7  902.58    15.6  899.64    23.4  891.46    31.2  883.76
      35   880.6   37.05879.3136      39  878.09    42.8   877.3   56.86877.0397
    58.4  877.02    62.3  877.02    66.2   877.5    70.1  878.53      74  878.51
    77.8  878.87    81.7  879.01    91.9 881.559      97  882.28   120.2     884
  126.72883.9771   131.7  884.04   139.4  883.71   143.2   884.2   147.1  885.06
   150.9   885.5   154.8  886.76   162.5  891.82   166.3  893.74   170.2  895.32
#Mann= 7 ,-1 , 0
       0      .1       0   37.05     .04       0   56.86      .1       0
    58.4     .04       0    77.8      .1       0    91.9    .016       0
  126.72     .12       0
Bank Sta=70.1,81.7
XS Rating Curve= 0 ,0
Exp/Cntr=0.3,0.1

Type RM Length L Ch R = 1 ,6381.1  ,91,80.7,83.6
XS GIS Cut Line= 4
     1749454.931      360587.697     1749520.505      360485.771
     1749513.908       360476.83     1749536.477      360442.108
#Sta/Elev= 30
       0  907.14     7.8  902.33    11.7   899.4    19.6  891.42    23.5  888.27
   31.15883.0069    35.2  881.42    39.1  880.99      43  881.07   55.52882.4136
   66.27883.0688    74.3  881.63    78.2   881.3    97.7  882.34   101.6  881.77
   105.6  880.38   110.1  877.62   117.3  872.13   121.2  870.26   124.9  869.92
   136.1  870.46   139.8  872.17   143.6   875.4   151.1  880.61   154.9  883.98
   158.7   888.2   162.4  891.84   166.2  894.17  172.23896.9765   173.7  897.64
#Mann= 8 ,-1 , 0
       0      .1       0   31.15     .04       0   55.52      .1       0
   66.27    .016       0   110.1      .1       0   121.2    .045       0
   136.1      .1       0  172.23     .12       0
Bank Sta=121.2,136.1
XS Rating Curve= 0 ,0
Exp/Cntr=0.3,0.1

Type RM Length L Ch R = 1 ,6300.4  ,228.3,228.8,229.2
XS GIS Cut Line= 2
     1749519.463      360621.361     1749608.021      360484.859
#Sta/Elev= 30
       0  905.56     7.9  900.34    11.9  896.88    19.8   888.6    23.8  886.08
    31.8  882.84    47.6  878.34    51.6   877.6    59.5  877.77    67.5  878.78
   71.35878.9083    79.4  879.03    87.3  879.53    91.3   879.1    95.2  876.94
   103.2  868.24   105.3  867.34   107.2  866.52   111.1  866.45   115.1  866.53
   119.1  867.32   120.3  867.96     123   869.4     127  872.62   134.9  880.16
  141.77885.5953   146.8  888.91   150.8  890.95   158.7  894.29   162.7  896.42
#Mann= 5 ,-1 , 0
       0      .1       0   71.35    .016       0   105.3    .045       0
   120.3      .1       0  141.77     .12       0
Bank Sta=105.3,120.3
XS Rating Curve= 0 ,0
Exp/Cntr=0.3,0.1

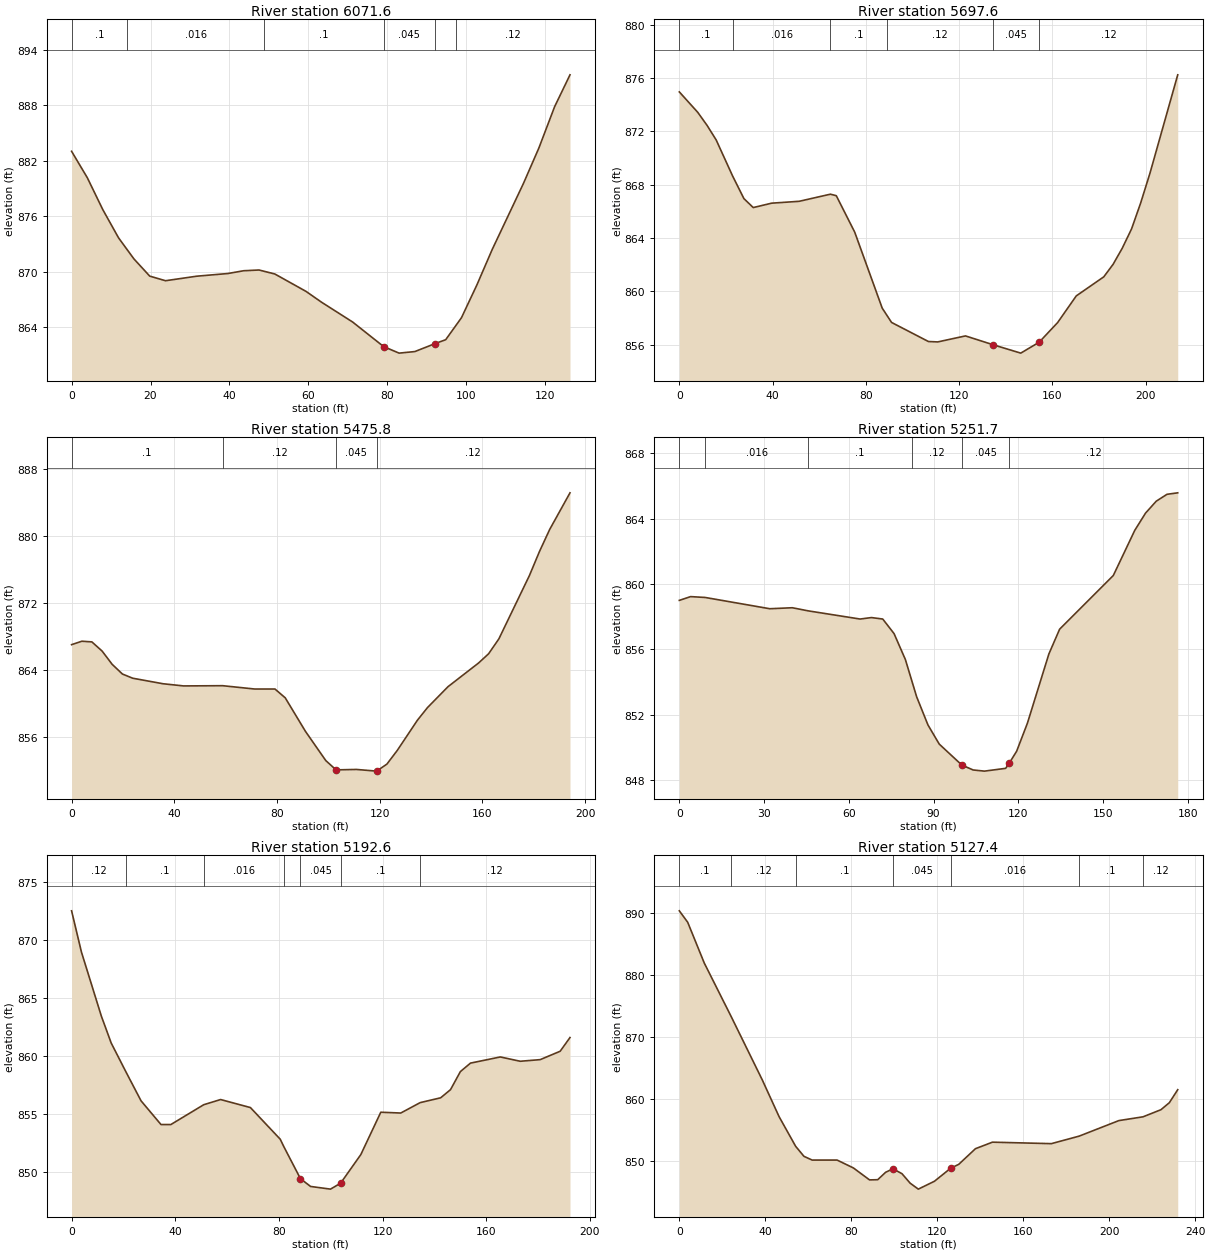
Type RM Length L Ch R = 1 ,6071.6  ,376.9,374,371.1
XS GIS Cut Line= 3
     1749727.685      360721.088     1749759.116       360670.65
     1749796.563      360615.241
#Sta/Elev= 30
       0  883.02       4  880.15     7.9  876.72    11.9  873.66   14.04872.4089
    15.8  871.38    19.8  869.52    23.8  869.02    31.7  869.51    39.6   869.8
    43.6   870.1    47.5  870.18   48.84870.0359    51.5  869.75    59.4  867.87
    63.4  866.68    71.2  864.56    79.1  861.89      83  861.19      87  861.36
    92.1  862.22    94.8  862.64   97.32864.1394    98.8  865.02   102.7  868.56
   106.6  872.41   114.5  879.54   118.4  883.36   122.4  887.84   126.3  891.29
#Mann= 6 ,-1 , 0
       0      .1       0   14.04    .016       0   48.84      .1       0
    79.1    .045       0    92.1      .1       0   97.32     .12       0
Bank Sta=79.1,92.1
XS Rating Curve= 0 ,0
Exp/Cntr=0.3,0.1

Type RM Length L Ch R = 1 ,5697.6  ,227.6,221.8,216
XS GIS Cut Line= 2
     1750016.685      360965.806     1750113.908      360775.528
#Sta/Elev= 30
       0  874.95     7.9  873.42    11.9  872.44    15.8  871.35   22.86868.6423
    27.7  866.95    31.7  866.28    39.6  866.61    51.4  866.75   64.78867.2834
    67.3  867.17    75.2  864.44      87  858.74    89.2858.1515      91  857.67
   106.8  856.24   110.8  856.21   122.7  856.66   134.5     856   146.4  855.37
   154.3  856.19   162.2  857.66   170.2  859.66     182  861.09     186  862.03
   189.9  863.23   193.9  864.68   197.8  866.62   201.8  868.86   213.7  876.23
#Mann= 6 ,-1 , 0
       0      .1       0   22.86    .016       0   64.78      .1       0
    89.2     .12       0   134.5    .045       0   154.3     .12       0
Bank Sta=134.5,154.3
XS Rating Curve= 0 ,0
Exp/Cntr=0.3,0.1

Type RM Length L Ch R = 1 ,5475.8  ,214.7,224.1,239.5
XS GIS Cut Line= 2
     1750259.741      361032.472     1750301.408      360842.889
#Sta/Elev= 30
       0  866.99       4   867.4     7.9  867.32    11.9  866.22    15.8  864.64
    19.8  863.48    23.8  862.98    35.6  862.32    43.6  862.06   58.87862.0859
    71.3  861.69    79.2  861.69    83.2  860.64    91.1  856.62      99  853.14
     103  852.03   110.9  852.08   118.8  851.88   122.8  852.72   126.8  854.34
   134.7  857.97   138.6  859.47   146.6  861.97   158.5   864.8   162.4   865.9
   166.4  867.68   178.3  875.25   182.2  878.11   186.2  880.76   194.1  885.13
#Mann= 4 ,-1 , 0
       0      .1       0   58.87     .12       0     103    .045       0
   118.8     .12       0
Bank Sta=103,118.8
XS Rating Curve= 0 ,0
Exp/Cntr=0.3,0.1

Type RM Length L Ch R = 1 ,5251.7  ,50.7,59.1,58.8
XS GIS Cut Line= 3
      1750423.63      361070.974     1750487.132      360983.669
     1750540.399      360940.639
#Sta/Elev= 30
       0     859       4  859.23    9.15859.1782      32  858.49      40  858.55
   45.67858.3582      64  857.86      68  857.95      72  857.86      76  856.97
      80  855.39   82.19854.1417      84  853.11      88  851.39      92  850.22
     100  848.94     104  848.64     108  848.57   115.5  848.74  116.75  849.05
   119.4  849.79   123.2   851.5   130.8  855.73   134.6  857.24   153.6  860.52
   161.2  863.28     165  864.33   168.8  865.06   172.6  865.48   176.4  865.57
#Mann= 6 ,-1 , 0
       0      .1       0    9.15    .016       0   45.67      .1       0
   82.19     .12       0     100    .045       0  116.75     .12       0
Bank Sta=100,116.75
XS Rating Curve= 0 ,0
Exp/Cntr=0.3,0.1

Type RM Length L Ch R = 1 ,5192.6  ,55.7,65.2,70.7
XS GIS Cut Line= 4
     1750493.074      361113.722     1750507.658      361034.556
     1750540.296      361022.056     1750570.158      360951.222
#Sta/Elev= 30
       0  872.48     3.8  868.94    11.5  863.42    15.3  861.11   20.96858.6417
    26.8  856.15    34.5  854.11    38.3  854.11   50.99 855.816    57.5  856.26
      69  855.57    80.5  852.85   81.95852.1844    88.3  849.46    92.2  848.79
    99.9  848.56   103.8  849.07   111.6  851.53   119.3  855.17     127   855.1
   134.5855.9954   142.4  856.41   146.2  857.11     150  858.66   153.9  859.39
   165.4  859.92   173.1  859.55   180.8  859.69   188.5  860.41   192.3  861.59
#Mann= 7 ,-1 , 0
       0     .12       0   20.96      .1       0   50.99    .016       0
   81.95      .1       0    88.3    .045       0   103.8      .1       0
   134.5     .12       0
Bank Sta=88.3,103.8
XS Rating Curve= 0 ,0
Exp/Cntr=0.3,0.1

Type RM Length L Ch R = 1 ,5127.4  ,192.1,161,136.4
XS GIS Cut Line= 4
     1750533.352      361146.361     1750546.546      361074.139
     1750601.408       361060.25     1750611.824      360958.861
#Sta/Elev= 30
       0   890.3     3.9  888.45    11.6  881.88   24.11 873.246    38.6  863.01
    46.4  857.09   54.13852.2874      58  850.67    61.8  850.07    73.4  850.07
      81   848.8    88.5  846.87    92.3   846.9      96   848.1    99.4  848.66
   103.6  847.87   107.4  846.34   111.2  845.38   118.7  846.65   126.2  848.74
     130  849.38   137.8  851.91   145.7  852.96   173.1  852.72  186.05853.9363
   204.5  856.44  215.75857.0523   224.1   858.2     228  859.33   231.9  861.43
#Mann= 7 ,-1 , 0
       0      .1       0   24.11     .12       0   54.13      .1       0
    99.4    .045       0   126.2    .016       0  186.05      .1       0
  215.75     .12       0
#XS Ineff= 2 , 0
       0    73.4                       0
Permanent Ineff=
       F       F
Bank Sta=99.4,126.2
XS Rating Curve= 0 ,0
Exp/Cntr=0.3,0.1