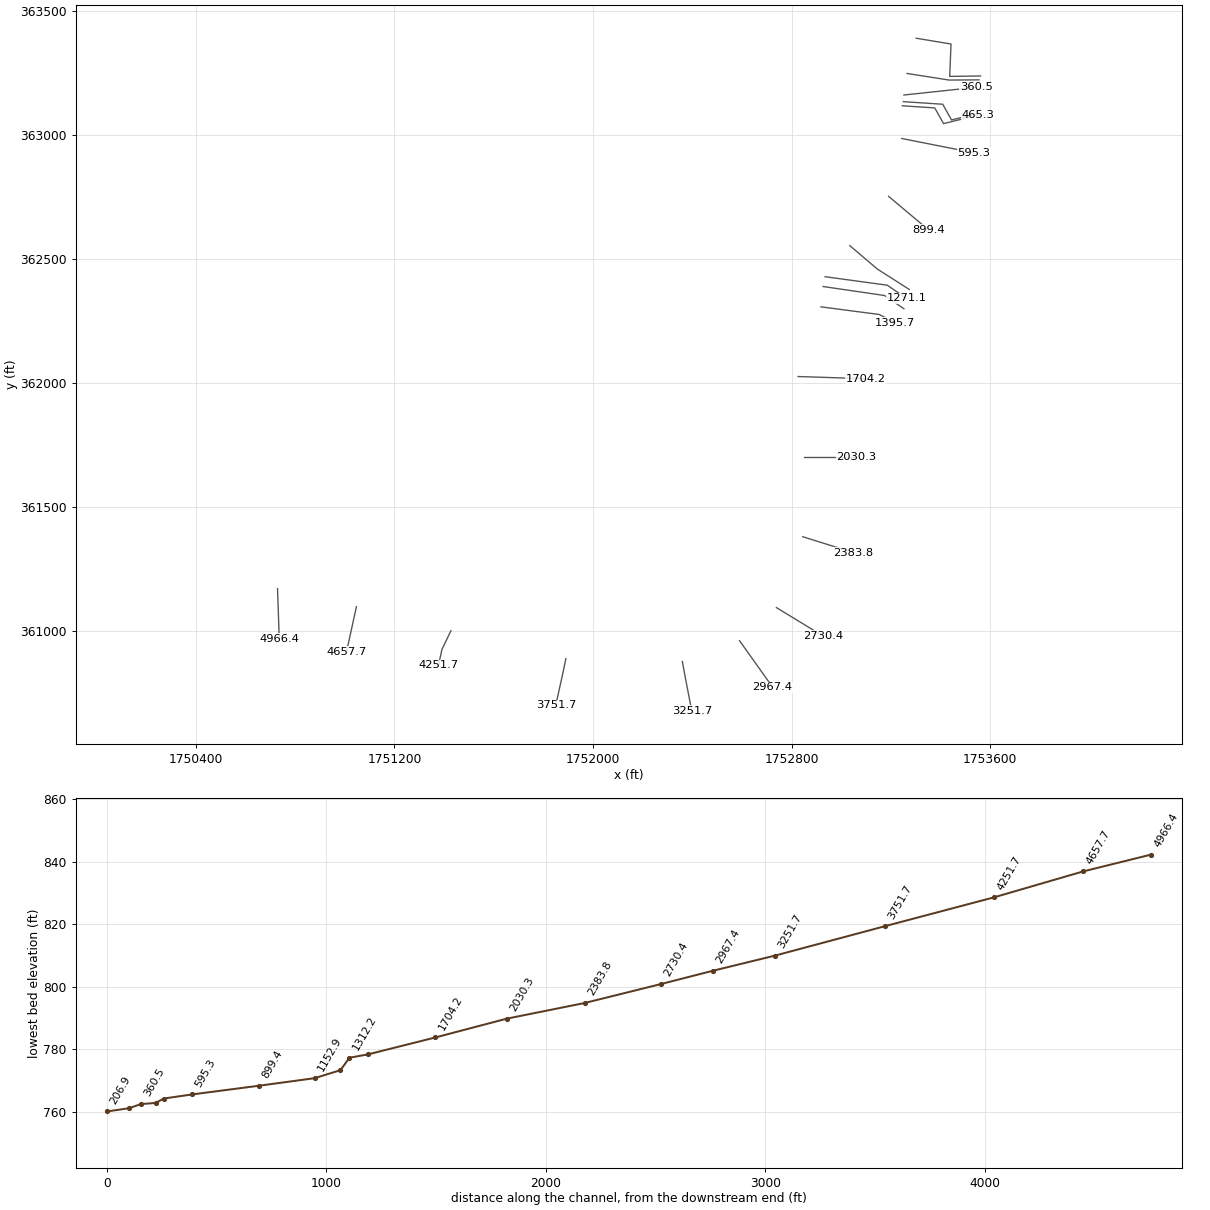
HEC-RAS study JACKSBR.prj: JACKSBR

--- JACKSBR.g01 (geometry) --- (continued)

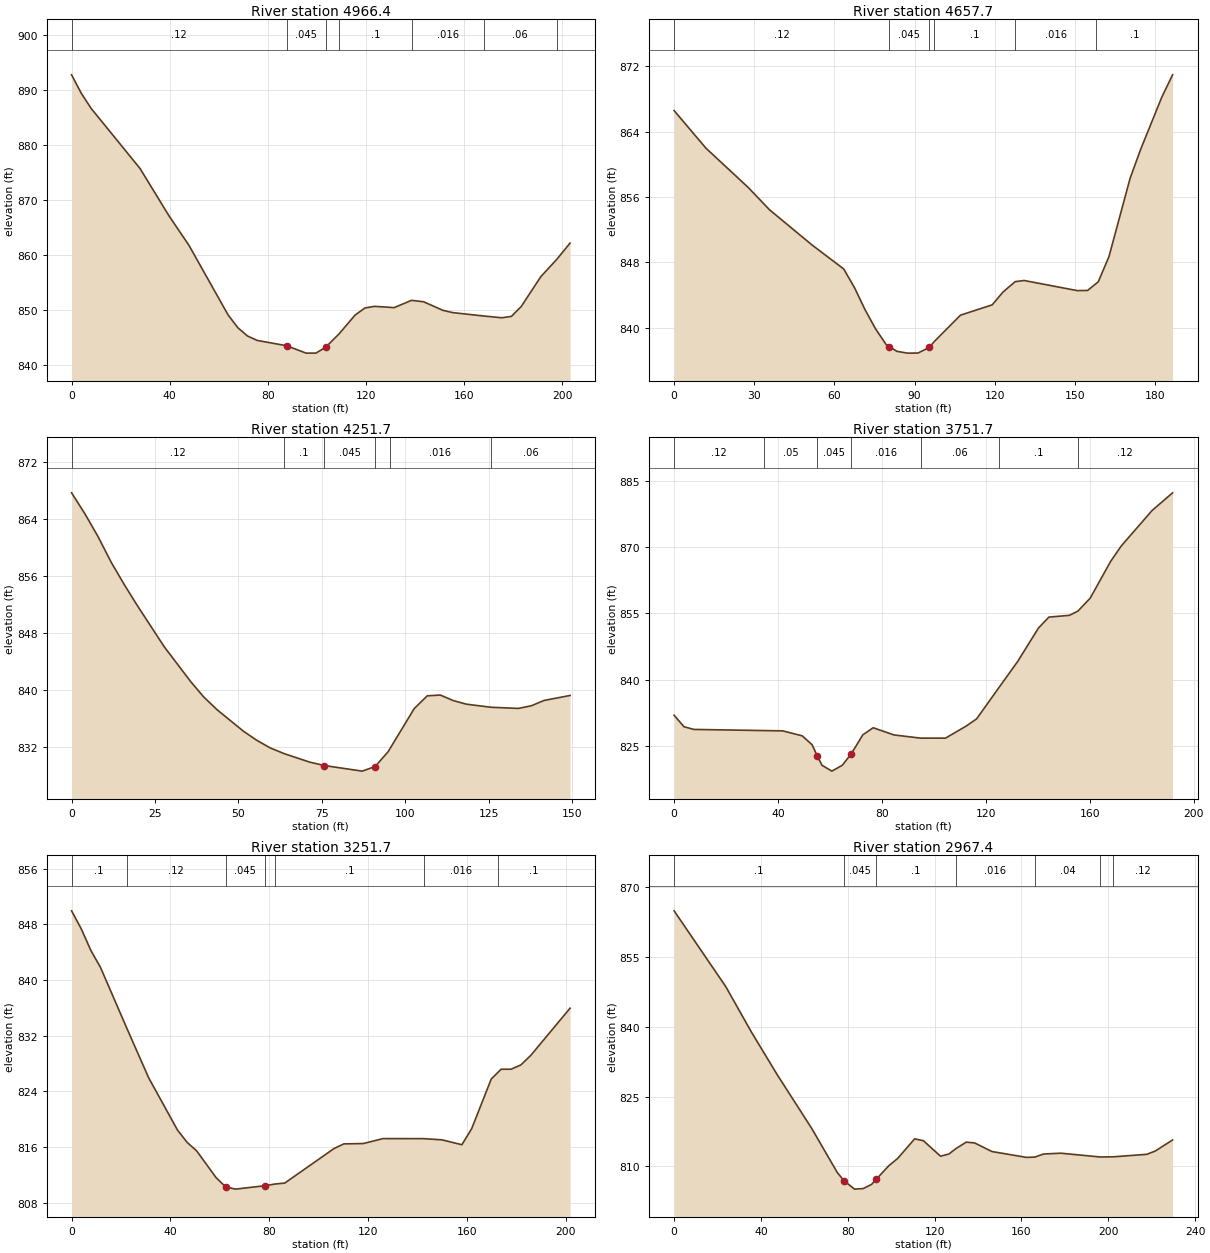
Type RM Length L Ch R = 1 ,4966.4  ,314.1,308.7,302.7
XS GIS Cut Line= 2
     1750729.185      361172.537      1750736.13      360969.412
#Sta/Elev= 30
       0  892.72       4  889.33       8  886.61    27.9  875.72    39.8  867.06
    47.8  861.81    63.8  849.14    67.8  846.81    71.7  845.32    75.7  844.51
    87.7  843.55    95.6  842.21    99.6  842.21   103.6  843.28  109.03 845.705
   115.6  849.13   119.6  850.41   123.5   850.7   131.5  850.47  138.59851.7917
   143.5  851.53   151.4  849.97   155.4  849.56  168.14848.9404   175.4  848.63
   179.3  848.88   183.3  850.68   191.3   856.1  197.69859.1832   203.2  862.18
#Mann= 7 ,-1 , 0
       0     .12       0    87.7    .045       0   103.6     .12       0
  109.03      .1       0  138.59    .016       0  168.14     .06       0
  197.69     .12       0
Bank Sta=87.7,103.6
XS Rating Curve= 0 ,0
Exp/Cntr=0.3,0.1

Type RM Length L Ch R = 1 ,4657.7  ,411.6,406,405.8
XS GIS Cut Line= 2
     1751047.079      361099.666     1751007.148      360917.375
#Sta/Elev= 30
       0  866.58    11.9  861.98    27.8  857.14    35.7  854.43    51.6  850.12
    63.5  847.17    67.5   844.9    71.5  842.17    75.4  839.84    79.4   837.9
    80.5  837.67    83.4  837.08    87.4  836.86    91.3  836.87    95.5  837.56
   97.44838.2952   107.2  841.51   119.1  842.78   123.1  844.34  127.67845.6149
     131  845.76   150.9  844.52   154.8  844.54  157.91845.3719   158.8  845.61
   162.8   848.7   170.7  858.28   174.7  861.87   182.6  868.25   186.6  870.96
#Mann= 6 ,-1 , 0
       0     .12       0    80.5    .045       0    95.5     .12       0
   97.44      .1       0  127.67    .016       0  157.91      .1       0
Bank Sta=80.5,95.5
XS Rating Curve= 0 ,0
Exp/Cntr=0.3,0.1

Type RM Length L Ch R = 1 ,4251.7  ,494,500,499.4
XS GIS Cut Line= 3
     1751427.874      361002.746      1751391.76      360927.743
     1751377.482      360863.118
#Sta/Elev= 30
       0  867.69       4  864.74     7.9  861.56    11.9  857.91    15.9  854.71
    19.8  851.78    27.8  846.04    35.7  841.17    39.6  839.01    43.6  837.22
    51.5   834.2    55.5  832.92    59.5  831.86   63.65831.0581    71.4  829.85
    75.7  829.38    87.1  828.59      91  829.24    94.9  831.34   95.41831.7375
   102.7  837.38   106.6  839.17   110.5  839.28   114.4   838.5   118.3     838
  125.66837.5637   133.9   837.4   137.8  837.77   141.6  838.52   149.4  839.22
#Mann= 6 ,-1 , 0
       0     .12       0   63.65      .1       0    75.7    .045       0
      91      .1       0   95.41    .016       0  125.66     .06       0
Bank Sta=75.7,91
XS Rating Curve= 0 ,0
Exp/Cntr=0.3,0.1

Type RM Length L Ch R = 1 ,3751.7  ,491.1,500,509.1
XS GIS Cut Line= 3
     1751890.958      360890.457     1751878.578      360831.006
     1751850.149      360703.005
#Sta/Elev= 30
       0  831.97     3.8  829.37     7.6  828.76    34.4   828.5    41.8  828.43
    49.3  827.31    53.1  825.29   55.04  822.81    56.9  820.65    60.7  819.32
    64.7  820.64    68.2  823.26    72.6  827.53    76.6  829.14    84.6  827.51
   94.84826.7889   104.4  826.78   112.4  829.52   116.4  831.15  125.09838.3141
   132.2  844.14   140.2  851.71   144.2  854.18   152.1  854.58  155.35855.5306
   160.1  858.47     168  866.82     172  870.25   183.9   878.3   191.8  882.31
#Mann= 7 ,-1 , 0
       0     .12       0    34.4     .05       0   55.04    .045       0
    68.2    .016       0   94.84     .06       0  125.09      .1       0
  155.35     .12       0
#XS Ineff= 2 , 0
       0                    76.2       0
Permanent Ineff=
       F       F
Bank Sta=55.04,68.2
XS Rating Curve= 0 ,0
Exp/Cntr=0.3,0.1

Type RM Length L Ch R = 1 ,3251.7  ,274.3,284.2,293.8
XS GIS Cut Line= 3
     1752360.095      360878.657      1752372.14      360813.414
     1752397.892      360680.436
#Sta/Elev= 30
       0  849.94     3.9  847.36     7.8  844.25    11.7  841.81   22.27833.1446
    31.2  825.95    42.9  818.42    46.8  816.66    50.7  815.42    58.5   811.6
    62.4  810.26    66.4  809.95    78.3  810.44   82.37810.6824    86.3  810.82
   106.2  815.77   110.2  816.45   118.1   816.5   126.1  817.21  142.53817.2034
     150  817.03     158  816.33     162  818.66   169.9  825.78  172.62 826.732
   173.9  827.18   177.9  827.18   181.9   827.8   185.9  829.17   201.8  835.95
#Mann= 7 ,-1 , 0
       0      .1       0   22.27     .12       0    62.4    .045       0
    78.3     .12       0   82.37      .1       0  142.53    .016       0
  172.62      .1       0
Bank Sta=62.4,78.3
XS Rating Curve= 0 ,0
Exp/Cntr=0.3,0.1

Type RM Length L Ch R = 1 ,2967.4  ,227.7,237.1,246.3
XS GIS Cut Line= 2
     1752590.482      360962.514      1752723.63      360775.528
#Sta/Elev= 30
       0  864.98    23.8  848.67    35.6   838.9    47.5  829.71    63.3  818.22
    75.2  808.64    78.2  806.92    83.1  805.09    87.1  805.21      91  806.12
    93.2  807.26    98.9  810.13   102.9  811.66   110.8  815.91   114.8  815.52
   122.7  812.18   126.6  812.65  129.84813.8245   134.6  815.21   138.5  815.02
   146.4  813.18   162.3  811.92   166.1811.9785   170.2  812.65   178.1  812.82
  196.34812.0063  202.36812.0468   217.7  812.58   221.6  813.28   229.6  815.67
#Mann= 7 ,-1 , 0
       0      .1       0    78.2    .045       0    93.2      .1       0
  129.84    .016       0   166.1     .04       0  196.34     .08       0
  202.36     .12       0
Bank Sta=78.2,93.2
XS Rating Curve= 0 ,0
Exp/Cntr=0.3,0.1

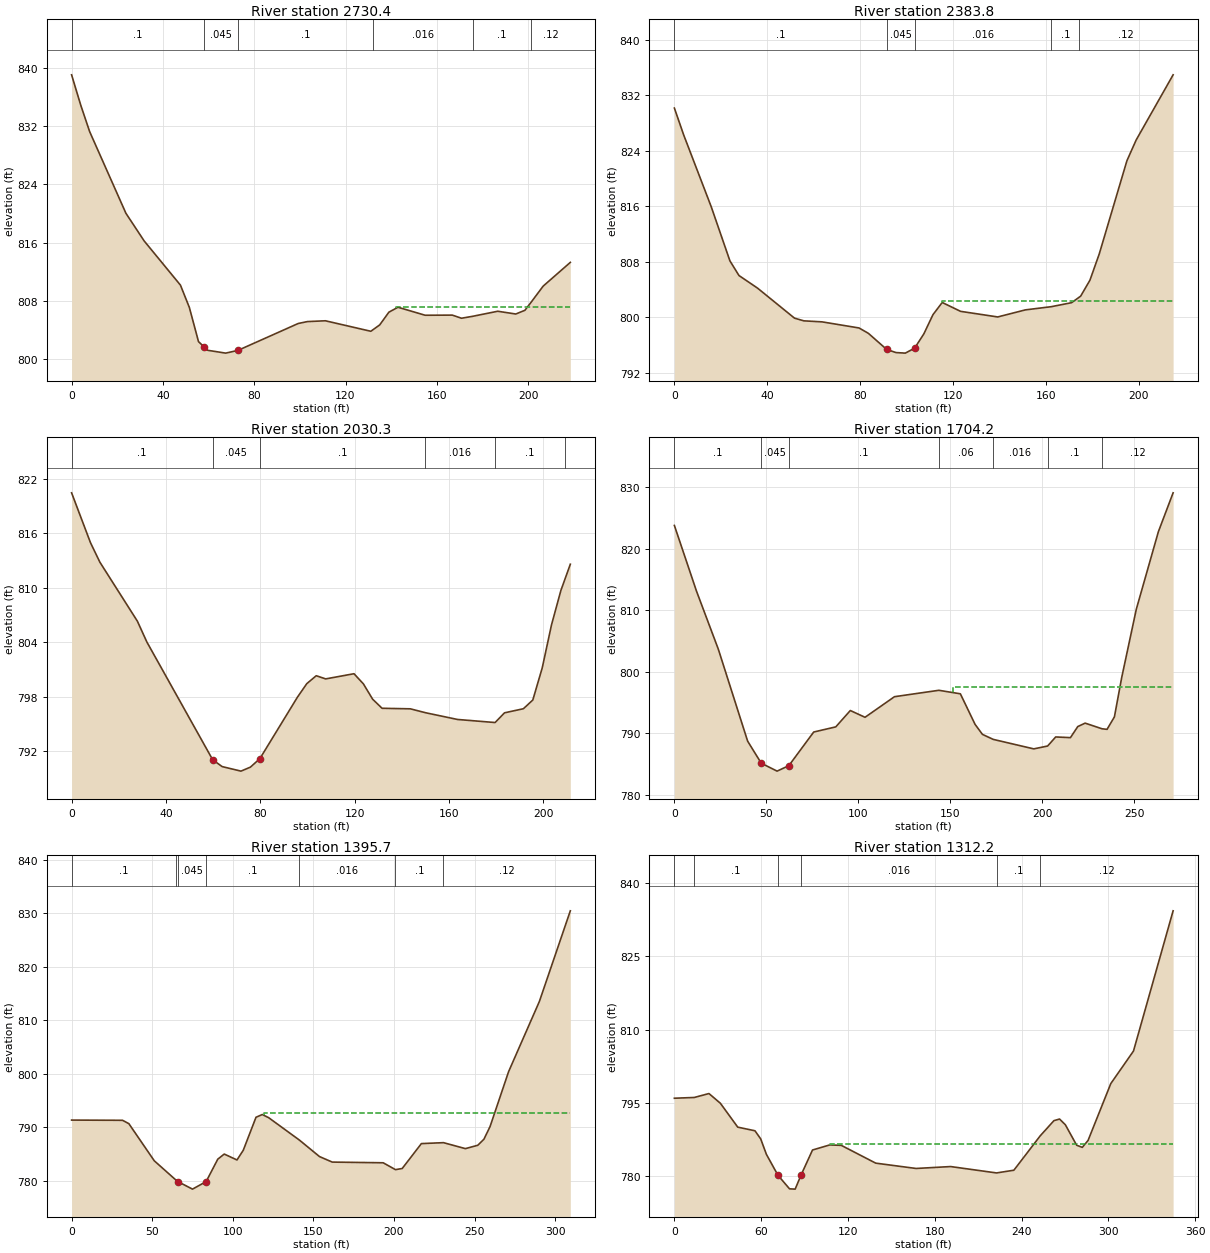
Type RM Length L Ch R = 1 ,2730.4  ,340.8,346.6,352.2
XS GIS Cut Line= 2
     1752739.178      361095.792     1752925.792        360982.2
#Sta/Elev= 30
       0  839.05       4  834.89     7.9  831.26    23.8  820.04    31.8  816.24
    47.7  810.17    51.6   807.1    55.6  802.42    57.9  801.74    59.6  801.23
    67.5  800.84    72.9  801.22    99.3  804.91   103.3  805.17   111.2  805.28
   131.1  803.84  132.14804.0747     135  804.72     139  806.46     143  807.14
   154.9  806.04   166.8  806.06   170.8  805.63  175.74805.8964   186.7  806.59
   194.6  806.21   198.6  806.72   201.3807.8203   206.6  810.04   218.5   813.3
#Mann= 6 ,-1 , 0
       0      .1       0    57.9    .045       0    72.9      .1       0
  132.14    .016       0  175.74      .1       0   201.3     .12       0
#XS Ineff= 2 , 0
                          142.02          807.19
Permanent Ineff=
       F       F
Bank Sta=57.9,72.9
XS Rating Curve= 0 ,0
Exp/Cntr=0.3,0.1

Type RM Length L Ch R = 1 ,2383.8  ,346.6,353.5,360.3
XS GIS Cut Line= 2
     1752844.941      361381.478     1753049.802      361317.241
#Sta/Elev= 30
       0  830.17       4   826.3    15.9   815.9    23.9  808.13    27.8  806.01
    35.8  804.19    51.7  799.86    55.7  799.47    63.6  799.32    79.5  798.44
    83.5  797.67    91.4  795.34    95.4  794.89    99.4  794.81   103.4  795.52
   107.4  797.59   111.3  800.35   115.3  802.12   123.2  800.84   139.2  800.03
   151.1  801.05  162.24801.5111     171  802.09  174.37802.9023   174.9  803.03
   178.9  805.34   182.9  809.12   194.8  822.56   198.8  825.57   214.7  834.97
#Mann= 5 ,-1 , 0
       0      .1       0    91.4    .045       0   103.4    .016       0
  162.24      .1       0  174.37     .12       0
#XS Ineff= 2 , 0
                          115.33           802.3
Permanent Ineff=
       F       F
Bank Sta=91.4,103.4
XS Rating Curve= 0 ,0
Exp/Cntr=0.3,0.1

Type RM Length L Ch R = 1 ,2030.3  ,326.9,326.1,325.4
XS GIS Cut Line= 2
     1752849.782       361700.95     1753061.209       361700.95
#Sta/Elev= 30
       0  820.43       8  814.95      12   812.8    27.9  806.31    31.9  804.03
    59.8  791.08    63.8  790.33    71.8  789.83    75.8  790.27    79.8   791.2
    95.7  797.95    99.7  799.45   103.7  800.32   107.7  799.97   119.7  800.54
   123.7  799.42   127.6  797.74   131.6  796.74   143.6  796.68  149.98796.2534
   163.6  795.51  179.51795.1727   183.5  796.24   191.5  796.69   195.5  797.65
   199.5  801.19   203.4  805.89   207.4   809.7  209.05 810.888   211.4  812.58
#Mann= 6 ,-1 , 0
       0      .1       0    59.8    .045       0    79.8      .1       0
  149.98    .016       0  179.51      .1       0  209.05     .12       0
Bank Sta=59.8,79.8
XS Rating Curve= 0 ,0
Exp/Cntr=0.3,0.1

Type RM Length L Ch R = 1 ,1704.2  ,311.1,308.5,305.8
XS GIS Cut Line= 2
     1752826.593       362026.75     1753097.426      362018.069
#Sta/Elev= 30
       0  823.79      12  813.12    23.9  803.64    39.8   788.7    47.2  785.11
    55.8  783.82    62.2  784.71    75.7  790.18    87.7  791.02    95.6  793.68
   103.6  792.58   119.6  795.93  143.71796.9708   155.4   796.4   163.4  791.42
   167.4   789.8  173.26788.9826   195.3  787.44  202.82787.9073   207.2  789.38
   215.2  789.27   219.2  791.07   223.2  791.63  232.37790.7087   235.1  790.62
   239.1  792.64   243.1   799.1     251  810.16     263  822.78     271   829.1
#Mann= 7 ,-1 , 0
       0      .1       0    47.2    .045       0    62.2      .1       0
  143.71     .06       0  173.26    .016       0  202.82      .1       0
  232.37     .12       0
#XS Ineff= 2 , 0
                          151.62          797.48
Permanent Ineff=
       F       F
Bank Sta=47.2,62.2
XS Rating Curve= 0 ,0
Exp/Cntr=0.3,0.1

Type RM Length L Ch R = 1 ,1395.7  ,82.8,83.5,83.2
XS GIS Cut Line= 3
       1752918.7      362307.432     1753153.373      362276.708
     1753218.074      362243.583
#Sta/Elev= 30
       0  791.31    31.6  791.27    35.5  790.65    51.3  783.69    64.9  780.04
   66.04  779.78      75  778.39   83.46   779.8    90.7     784    94.7  784.95
   102.6  783.85   106.5  785.66   114.4  791.84   118.3  792.35   122.3  791.75
  141.35787.5634   153.8  784.48   161.7  783.45   193.3  783.32  200.92782.0369
   205.1  782.25     217  786.91  230.71787.0845   244.3  785.97     252   786.6
   255.8  787.73   259.6   790.1   271.1  800.37   290.2  813.51   309.4  830.47
#Mann= 7 ,-1 , 0
       0      .1       0    64.9    .045       0   66.04    .045       0
   83.46      .1       0  141.35    .016       0  200.92      .1       0
  230.71     .12       0
#XS Ineff= 2 , 0
                          119.29           792.7
Permanent Ineff=
       F       F
Bank Sta=66.04,83.46
XS Rating Curve= 0 ,0
Exp/Cntr=0.3,0.1

Type RM Length L Ch R = 1 ,1312.2  ,41.7,41.1,41.3
XS GIS Cut Line= 3
     1752927.102      362389.417     1753175.092      362353.114
     1753252.796      362299.833
#Sta/Elev= 30
       0  795.95   13.75796.1066    23.9  796.91    31.8  794.92    43.8  790.03
    55.7  789.29    59.7  787.61    63.6  784.47    71.6  780.18    79.6   777.4
    83.5  777.34    87.5  780.17    95.5  785.35   107.4  786.39   115.4   786.3
   139.2  782.66   167.1  781.57     191  781.96  222.71 780.655   234.7  781.21
  252.94788.2588   262.4  791.36   266.3  791.69   270.3  790.52   278.1  786.33
     282  785.89     286  787.31   301.7  798.94   317.4  805.61   344.8  834.32
#Mann= 6 ,-1 , 0
       0    .016       0   13.75      .1       0    71.6    .045       0
    87.5    .016       0  222.71      .1       0  252.94     .12       0
#XS Ineff= 2 , 0
                          107.64          786.68
Permanent Ineff=
       F       F
Bank Sta=71.6,87.5
XS Rating Curve= 0 ,0
Exp/Cntr=0.3,0.1

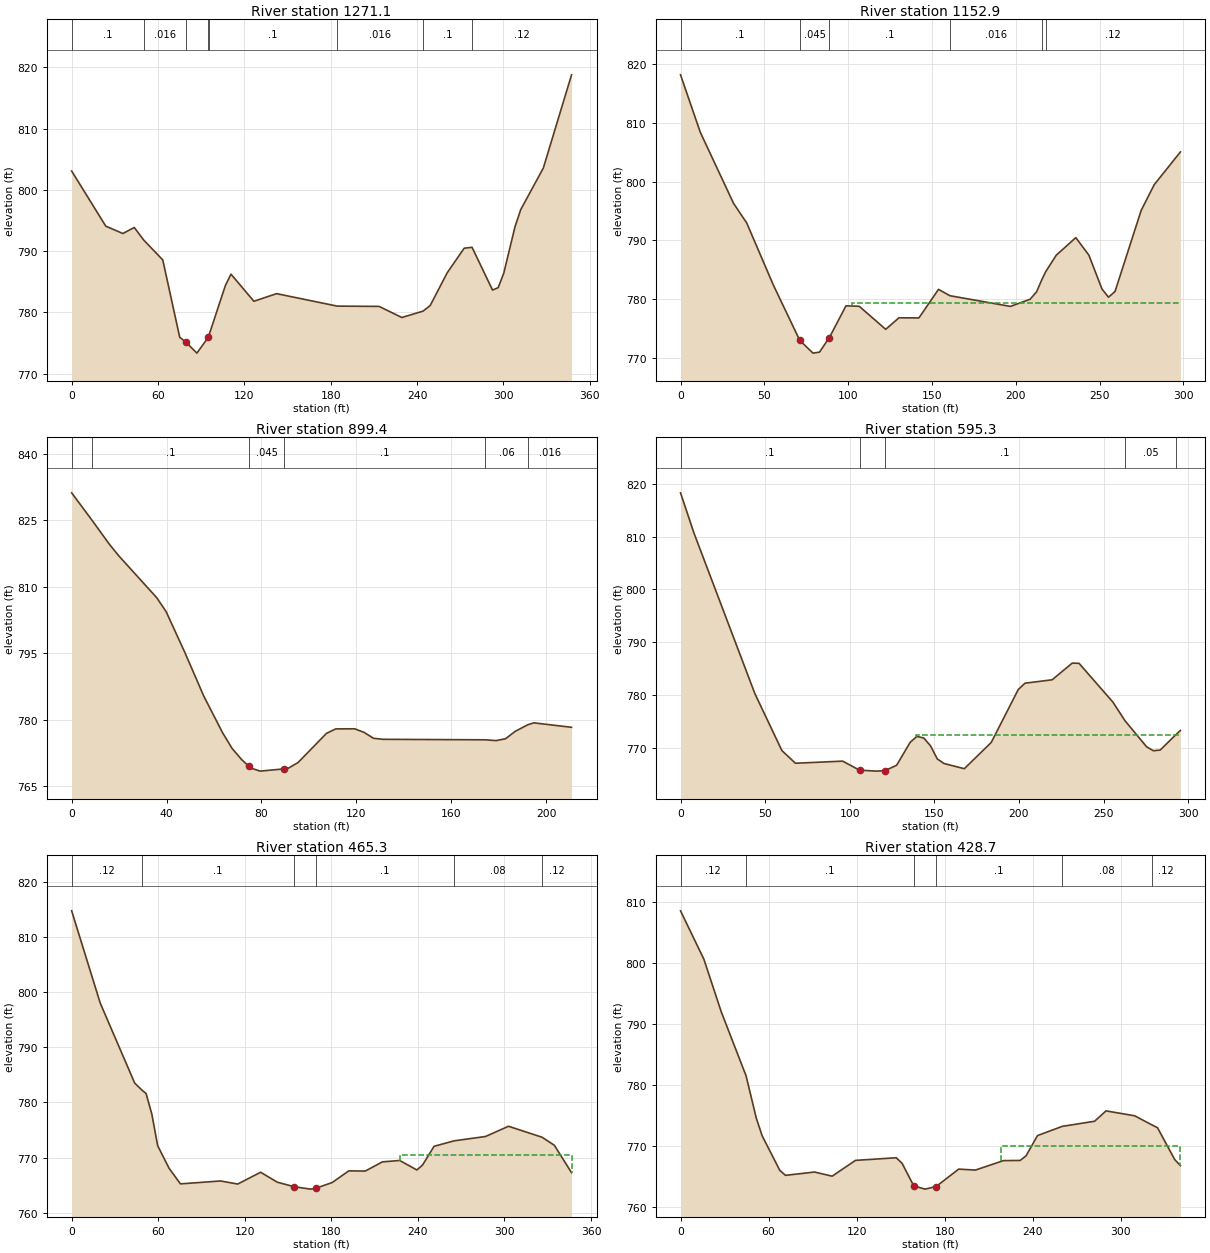
Type RM Length L Ch R = 1 ,1271.1  ,131.6,118.2,104.8
XS GIS Cut Line= 3
     1752935.088      362428.913     1753185.856      362394.694
      1753263.56      362341.413
#Sta/Elev= 30
       0  803.07    23.7  794.08    35.6  792.88    43.5  793.86   50.17 791.785
    63.3  788.57    75.1  775.94    79.1  775.22      87  773.37    94.9  775.94
    95.1776.0765   106.8   784.4   110.7  786.25   126.6  781.83   142.4  783.07
  184.53781.0372   213.6  780.99   229.4  779.18  244.15780.2213   249.1  781.14
   260.9  786.47   272.7  790.48  278.16790.6337   292.4  783.66   296.3  784.04
   300.2   786.4     308  793.97     312  796.78   327.7  803.56   347.3  818.76
#Mann= 8 ,-1 , 0
       0      .1       0   50.17    .016       0    79.1    .045       0
    94.9    .016       0    95.1      .1       0  184.53    .016       0
  244.15      .1       0  278.16     .12       0
#XS Ineff= 2 , 0
       0                   110.7       0
Permanent Ineff=
       F       F
Bank Sta=79.1,94.9
XS Rating Curve= 0 ,0
Exp/Cntr=0.3,0.1

Type RM Length L Ch R = 1 ,1152.9  ,253.3,253.5,253.7
XS GIS Cut Line= 3
     1753034.741         362554.     1753146.152      362459.494
     1753274.324      362377.611
#Sta/Elev= 30
       0  818.15    11.8  808.37    31.6   796.3    39.5  792.94    55.3  782.43
    71.1  772.99      79   770.8    82.9  770.97    88.8  773.45    98.7  778.85
   106.6  778.77   122.4  774.85   130.3  776.81   142.2  776.79   153.9  781.65
  160.65780.5715   196.8  778.75   208.5  779.96   212.4  781.23  215.51783.2874
  217.75784.6093   224.1  787.45   235.8  790.45   243.6  787.47   251.4  781.72
   255.3  780.32   259.2  781.29   274.8  795.09   282.6  799.47   298.2  805.03
#Mann= 6 ,-1 , 0
       0      .1       0    71.1    .045       0    88.8      .1       0
  160.65    .016       0  215.51      .1       0  217.75     .12       0
#XS Ineff= 2 , 0
                          102.25          779.28
Permanent Ineff=
       F       F
Bank Sta=71.1,88.8
XS Rating Curve= 0 ,0
Exp/Cntr=0.3,0.1

Type RM Length L Ch R = 1 ,899.4   ,292.7,304.1,314.8
XS GIS Cut Line= 2
     1753191.176      362752.444     1753352.635      362617.027
#Sta/Elev= 30
       0  831.19    8.45825.0961    15.9  819.59    19.9  816.95    35.8  807.56
    39.8   804.4    47.7  795.18    55.7   785.3    63.6  777.07    67.6  773.53
    71.6  771.02    74.7  769.48    75.5  769.08    79.5  768.39    89.7  768.91
    91.4  769.07    95.4  770.32   107.4  776.91   111.3  777.92   119.3  777.94
   123.3  777.12   127.2   775.8   131.2  775.57  174.25775.4567   178.9  775.28
   182.9   775.7   186.9  777.35   192.3778.8675   194.8  779.28   210.7  778.28
#Mann= 6 ,-1 , 0
       0     .12       0    8.45      .1       0    74.7    .045       0
    89.7      .1       0  174.25     .06       0   192.3    .016       0
Bank Sta=74.7,89.7
XS Rating Curve= 0 ,0
Exp/Cntr=0.3,0.1

Type RM Length L Ch R = 1 ,595.3   ,149.6,130,109.2
XS GIS Cut Line= 2
      1753244.29      362985.731     1753534.046      362928.306
#Sta/Elev= 30
       0  818.27       8  810.61    43.9  780.31    59.9  769.51    67.9  767.11
    95.8  767.51   105.8   765.8   115.8  765.62   120.8  765.71   127.7  766.73
   135.7  771.07   139.7  772.19   143.7  771.89   147.7  770.43   151.7  767.94
   155.7  767.06   167.7  766.08   183.6  771.04   199.6  781.07   203.6  782.26
   219.6   782.9   231.5  786.06   235.5  786.01   255.5  778.68  262.63775.1611
   275.4  770.23   279.4  769.48   283.4   769.6  292.74772.5253   295.4  773.31
#Mann= 5 ,-1 , 0
       0      .1       0   105.8    .045       0   120.8      .1       0
  262.63     .05       0  292.74     .06       0
#XS Ineff= 2 , 0
                          139.28          772.42
Permanent Ineff=
       F       F
Bank Sta=105.8,120.8
XS Rating Curve= 0 ,0
Exp/Cntr=0.3,0.1

Type RM Length L Ch R = 1 ,465.3   ,23.5,36.6,37.5
XS GIS Cut Line= 4
     1753246.402      363117.484     1753377.131       363108.89
     1753412.548      363045.609      1753551.35      363079.984
#Sta/Elev= 30
       0  814.72    19.8  798.01    43.7  783.51   48.87782.2001    51.6  781.62
    55.6  777.86    59.6  772.18    67.5  768.09    75.4  765.25   103.2  765.78
   115.1  765.22     131  767.36   142.5  765.56   153.9  764.76   165.4   764.3
   169.2  764.45   180.6   765.5   192.1  767.61   203.5  767.57   215.4  769.24
   227.4  769.49   239.3  767.77   243.2  768.66   251.2  772.06  265.16773.0515
   286.9  773.84   302.8  775.69  326.02773.7063   334.6  772.24   346.5  767.28
#Mann= 6 ,-1 , 0
       0     .12       0   48.87      .1       0   153.9    .045       0
   169.2      .1       0  265.16     .08       0  326.02     .12       0
#XS Ineff= 2 , 0
                          227.55          770.44
Permanent Ineff=
       F       F
Bank Sta=153.9,169.2
XS Rating Curve= 0 ,0
Exp/Cntr=0.3,0.1

Type RM Length L Ch R = 1 ,428.7   ,54.2,68.2,95.2
XS GIS Cut Line= 4
     1753250.568      363134.151     1753409.162      363123.734
     1753444.579      363060.453     1753550.568      363086.494
#Sta/Elev= 30
       0   808.5    15.9  800.58    27.8  791.92   44.69781.4442    51.6  774.55
    55.6  771.65    67.6  765.99    71.5  765.16    91.4   765.7   103.3  765.02
   119.2  767.61     147  768.04     151  767.12   158.9  763.43   166.6   762.9
   174.2  763.33   189.5  766.18   200.9  766.02     220  767.57   231.4   767.6
   235.4  768.35   243.2  771.67  260.08773.1841   282.1  774.02   289.9  775.72
   309.4  774.92  320.91773.4575     325  772.96   336.7  767.75   340.6  766.75
#Mann= 6 ,-1 , 0
       0     .12       0   44.69      .1       0   158.9    .045       0
   174.2      .1       0  260.08     .08       0  320.91     .12       0
#XS Ineff= 2 , 0
                          218.52          769.97
Permanent Ineff=
       F       F
Bank Sta=158.9,174.2
XS Rating Curve= 0 ,0
Exp/Cntr=0.3,0.1

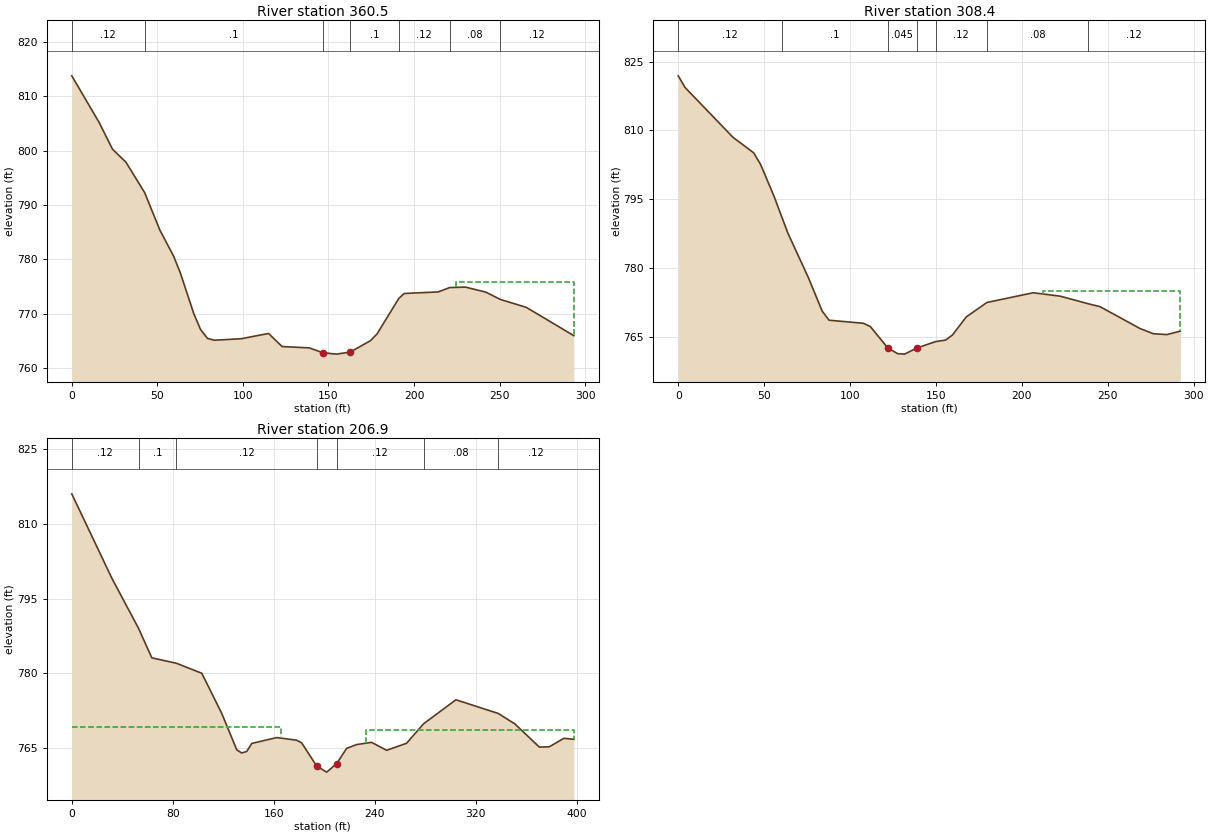
Type RM Length L Ch R = 1 ,360.5   ,57.8,52.1,46.4
XS GIS Cut Line= 2
     1753252.796      363160.945      1753544.55      363192.068
#Sta/Elev= 30
       0  813.79    15.9  805.25    23.8  800.28    31.7  797.87   42.61792.2589
    51.5  785.36    59.5  780.58    63.4  777.52    71.4  769.89    75.3  767.03
    79.3  765.42    83.3  765.08    99.1  765.36     115  766.33   122.9  763.92
   138.8  763.67   146.7  762.78   154.6  762.52   162.6  762.89   174.5  764.98
   178.4  766.24  191.13772.7945   194.3  773.69   214.1  773.98  220.83  774.78
     230  774.87   241.9  773.95  250.53772.5861   265.6  771.14   293.4  765.92
#Mann= 7 ,-1 , 0
       0     .12       0   42.61      .1       0   146.7    .045       0
   162.6      .1       0  191.13     .12       0  220.83     .08       0
  250.53     .12       0
#XS Ineff= 2 , 0
                          224.49          775.82
Permanent Ineff=
       F       F
Bank Sta=146.7,162.6
XS Rating Curve= 0 ,0
Exp/Cntr=0.3,0.1

Type RM Length L Ch R = 1 ,308.4   ,135.9,101.5,52.5
XS GIS Cut Line= 3
     1753265.296       363247.75     1753434.837      363221.191
     1753555.401      363222.016
#Sta/Elev= 30
       0  821.88       4  819.33    31.9  808.47    43.9   805.1    47.9  802.59
    55.9  795.49   60.13791.2612    63.8  787.61    75.8  777.84    83.8  770.58
    87.8  768.61   107.8  767.94   111.8  767.23  121.98  762.56   127.7  761.32
   131.7  761.22   138.7  762.53  149.82763.9561   155.6  764.28   159.6  765.39
   167.6  769.32  179.62772.4749   206.6   774.6   222.2  773.86  238.69772.1945
   245.5  771.56   268.8  766.79   276.6  765.66   284.4  765.48   292.2  766.24
#Mann= 7 ,-1 , 0
       0     .12       0   60.13      .1       0  121.98    .045       0
   138.7      .1       0  149.82     .12       0  179.62     .08       0
  238.69     .12       0
#XS Ineff= 2 , 0
                          212.14          775.04
Permanent Ineff=
       F       F
Bank Sta=121.98,138.7
XS Rating Curve= 0 ,0
Exp/Cntr=0.3,0.1

Type RM Length L Ch R = 1 ,206.9   ,98.5,65.7,76.6
XS GIS Cut Line= 4
     1753301.957      363389.793     1753442.582      363366.355
     1753437.258      363235.905     1753561.824      363237.641
#Sta/Elev= 30
       0  816.04    31.7  799.13   53.01788.9869    63.4  783.12   82.95782.0237
     103  780.02   118.8  771.96   130.7  764.66   134.6  764.02   138.6  764.34
   142.6  765.94   162.4  767.12   178.2  766.58   182.1  766.06     194  761.39
   201.9  760.18   209.8  761.88   217.7  764.94   225.6  765.71   237.5  766.16
   249.4  764.56   265.2  765.97  278.71769.8936   304.3   774.7  337.79771.9597
     351  769.86   370.4   765.2   378.2  765.26   389.9  766.97   397.7  766.77
#Mann= 7 ,-1 , 0
       0     .12       0   53.01      .1       0   82.95     .12       0
     194    .045       0   209.8     .12       0  278.71     .08       0
  337.79     .12       0
#XS Ineff= 2 , 0
          165.94  769.22  232.82          768.72
Permanent Ineff=
       F       F
Bank Sta=194,209.8
XS Rating Curve= 0 ,0
Exp/Cntr=0.3,0.1