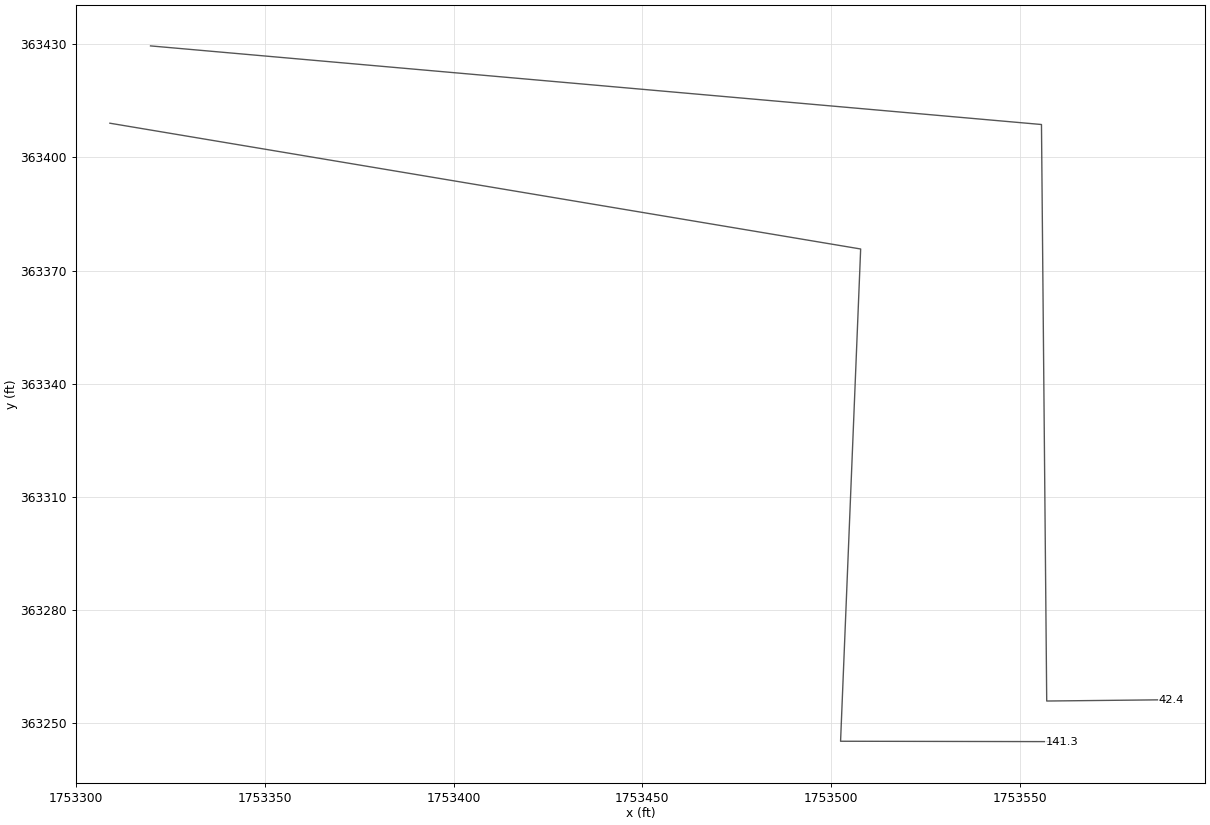
HEC-RAS study JACKSBR.prj: JACKSBR

--- JACKSBR.g01 (geometry) --- (continued)

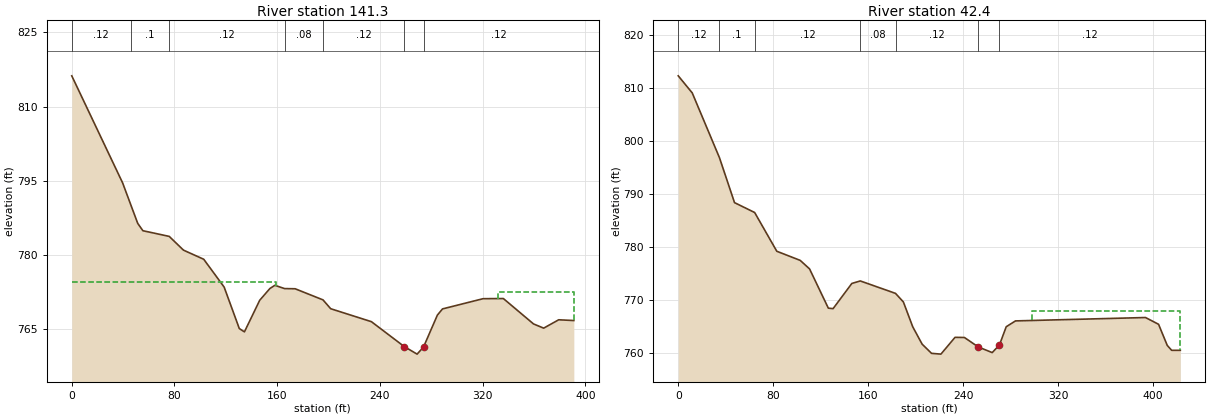
Type RM Length L Ch R = 1 ,141.3   ,64.2,98.9,100.1
XS GIS Cut Line= 4
     1753308.902      363409.064      1753507.86       363375.73
     1753502.536       363245.28     1753561.332      363245.175
#Sta/Elev= 30
       0  816.22    39.6  794.56   45.97790.1207    51.4  786.35    55.4  784.87
   75.92783.7205      87  780.94   102.8  779.09   118.7  773.46   130.5  765.07
   134.5   764.4   146.4  770.79   154.3  773.16   158.2  773.82  165.76773.1536
     174  773.12  195.71770.8685   201.7  769.08   233.4  766.46     259  761.42
     269  759.89     274  761.32   284.8  767.79   288.8  769.04   320.4  771.11
   336.2  771.14   359.7     766   367.6  765.15   379.3  766.84   391.1  766.69
#Mann= 7 ,-1 , 0
       0     .12       0   45.97      .1       0   75.92     .12       0
  165.76     .08       0  195.71     .12       0     259    .045       0
     274     .12       0
#XS Ineff= 2 , 0
          159.45  774.47  331.83          772.56
Permanent Ineff=
       F       F
Bank Sta=259,274
XS Rating Curve= 0 ,0
Exp/Cntr=0.3,0.1

Type RM Length L Ch R = 1 ,42.4    ,44.3,42.4,40.4
XS GIS Cut Line= 4
     1753319.666       363429.55     1753555.777      363408.717
     1753557.166      363255.939     1753590.152      363256.286
#Sta/Elev= 30
       0  812.37    11.8  809.14   34.71796.9193    47.4  788.43   64.36786.5656
      83  779.25   102.7  777.53   110.6  775.92   126.4  768.51   130.4  768.42
   146.2  773.17  153.32773.6453  182.97771.2993   189.6  769.68   197.5  764.98
   205.4  761.71   213.3  759.98   221.2  759.83   233.1     763     241  762.97
   252.7  761.18   264.4  760.12   270.5  761.56   276.2     765     284   766.1
   393.5  766.74   404.5  765.46   411.8  761.48   415.5  760.55   422.8  760.55
#Mann= 7 ,-1 , 0
       0     .12       0   34.71      .1       0   64.36     .12       0
  153.32     .08       0  182.97     .12       0   252.7    .045       0
   270.5     .12       0
#XS Ineff= 2 , 0
                          298.25          767.97
Permanent Ineff=
       F       F
Bank Sta=252.7,270.5
XS Rating Curve= 0 ,0
Exp/Cntr=0.3,0.1

Chan Stop Cuts=-1
Use User Specified Reach Order=0
Composite Channel Slope=5